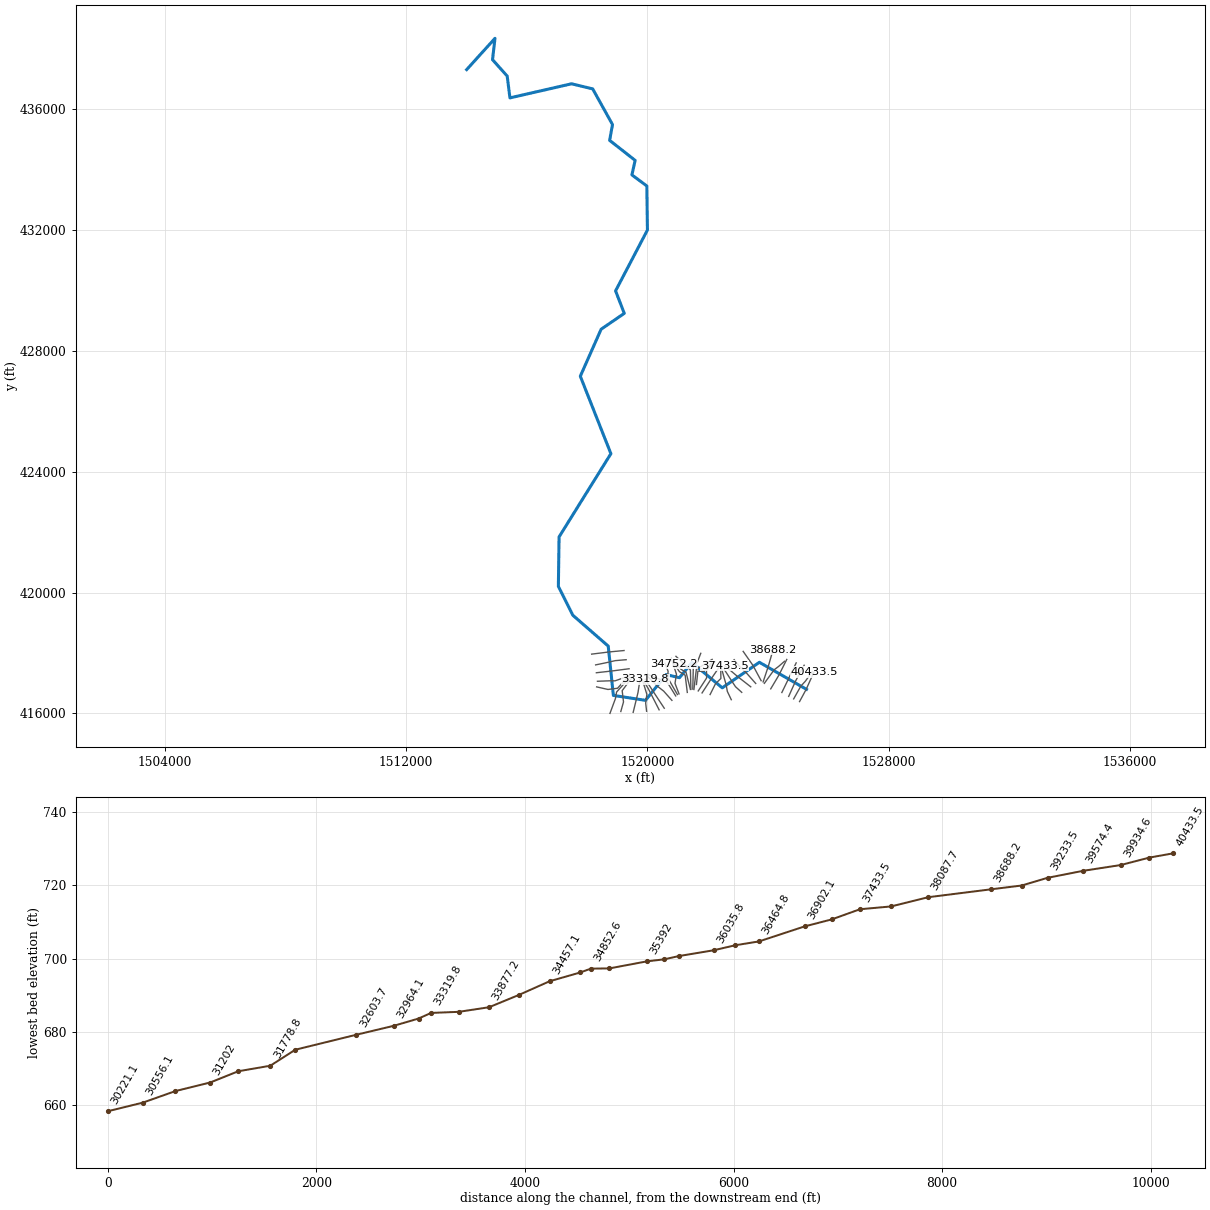
--- HURICANCR.prj (project) ---

Proj Title=HURICANCR
Current Plan=p01
Default Exp/Contr=0,0
English Units
Geom File=g01
Flow File=f01
Plan File=p01
BEGIN DESCRIPTION:
END DESCRIPTION:
DSS Export Rating Curves= 0
DSS Export Rating Curve Sorted= 0
DSS Export Volume Flow Curves= 0
DXF OffsetX= 0
DXF OffsetY= 0
DXF ScaleX= 0
DXF ScaleY= 0

--- HURICANCR.p01 (plan) ---

Plan Title=Floodplain
Program Version=4.00
Geom File=g01
Flow File=f01
K Sum by GR=0
Std Step Tol=0.01
Critical Tol=0.01
Num of Std Step Trials=20
Max Error Tol=0.3
Flow Tol Ratio=0.001
Split Flow NTrial=30
Split Flow Tol=0.02
Split Flow Ratio=0.02
Log Output Level=0
Friction Slope Method=1
Unsteady Friction Slope Method=2
Unsteady Bridges Friction Slope Method=1
Global Log Level=0
CheckData=False
Run HTab=0
Run UNet=0
Run PostProcess=0
UNET Theta=0
UNET Theta Warmup=0
UNET ZTol=0
UNET ZSATol=0
UNET MxIter=0
UNET MaxInSteps=0
UNET DtIC=0
UNET DtMin=0
UNET MaxCRTS=0
UNET WFStab=0
UNET SFStab=0
UNET WFX=0
UNET SFX=0
UNET DSS MLevel=0
UNET DZMax Abort=0
UNET Convert EG Bridges=0
UNET Use Existing IB Tables=0
UNET Froude Limit=0
UNET Froude Power=0
Write IC File=0
Echo Input=False
Echo Output=False
Write Detailed=0

--- HURICANCR.f01 (steady flow) ---

Flow Title=NFF Regression Equation
Program Version=4.00
Number of Profiles= 1
Profile Names=P100yr
River Rch & RM=HURICANCR,Main            ,40433.5
     368
River Rch & RM=HURICANCR,Main            ,38985
     384
River Rch & RM=HURICANCR,Main            ,38688.2
     557
River Rch & RM=HURICANCR,Main            ,38087.7
     602
River Rch & RM=HURICANCR,Main            ,36902.1
     657
River Rch & RM=HURICANCR,Main            ,33200.6
     719
River Rch & RM=HURICANCR,Main            ,32964.1
     804
River Rch & RM=HURICANCR,Main            ,31778.8
     814
River Rch & RM=HURICANCR,Main            ,31471.3
     948
River Rch & RM=HURICANCR,Main            ,30869.7
     956
River Rch & RM=HURICANCR,Main            ,28468.6
    1058
River Rch & RM=HURICANCR,Main            ,22471.9
    1171
River Rch & RM=HURICANCR,Main            ,22178.1
    1308
River Rch & RM=HURICANCR,Main            ,17670.8
    1375
River Rch & RM=HURICANCR,Main            ,15872.4
    1527
River Rch & RM=HURICANCR,Main            ,12269.7
    1580
River Rch & RM=HURICANCR,Main            ,11977.1
    1934
River Rch & RM=HURICANCR,Main            ,2032.1
    2121
River Rch & RM=HURICANCR,Main            ,1745.5
    2537
Boundary for River Rch & Prof#=HURICANCR,Main            , 1
Up Type= 0
Dn Type= 3
Dn Slope=0.0013
DSS Import GetInterval= 0
DSS Import GetPeak= 0
DSS Import FillOption= 0

--- HURICANCR.g01 (geometry) ---

Geom Title=USGS 10m DEM
Program Version=4.00

River Reach=HURICANCR       ,Main
Reach XY= 30
      1525274.98       416795.95     1523713.702      417691.481
     1522483.959      416845.694     1521476.404      417681.739
     1521065.047      417180.235     1520624.807      417284.886
      1519940.94      416431.513     1518874.742      416595.149
     1518704.823      418227.761     1517532.699      419248.104
     1517051.932      420205.312     1517075.343      421843.456
     1518792.788      424599.656     1517779.346      427163.915
     1518469.899      428721.247       1519236.4      429245.028
     1518947.632      429990.352     1520003.696      432004.951
     1519984.073      433464.209     1519489.578      433830.435
     1519595.907      434311.879     1518751.376      434974.634
     1518845.944      435498.158      1518189.34      436678.911
     1517488.627      436847.615     1515446.895       436381.08
     1515355.681      437103.551     1514869.622      437646.228
     1514951.286      438352.997     1514012.519      437316.437

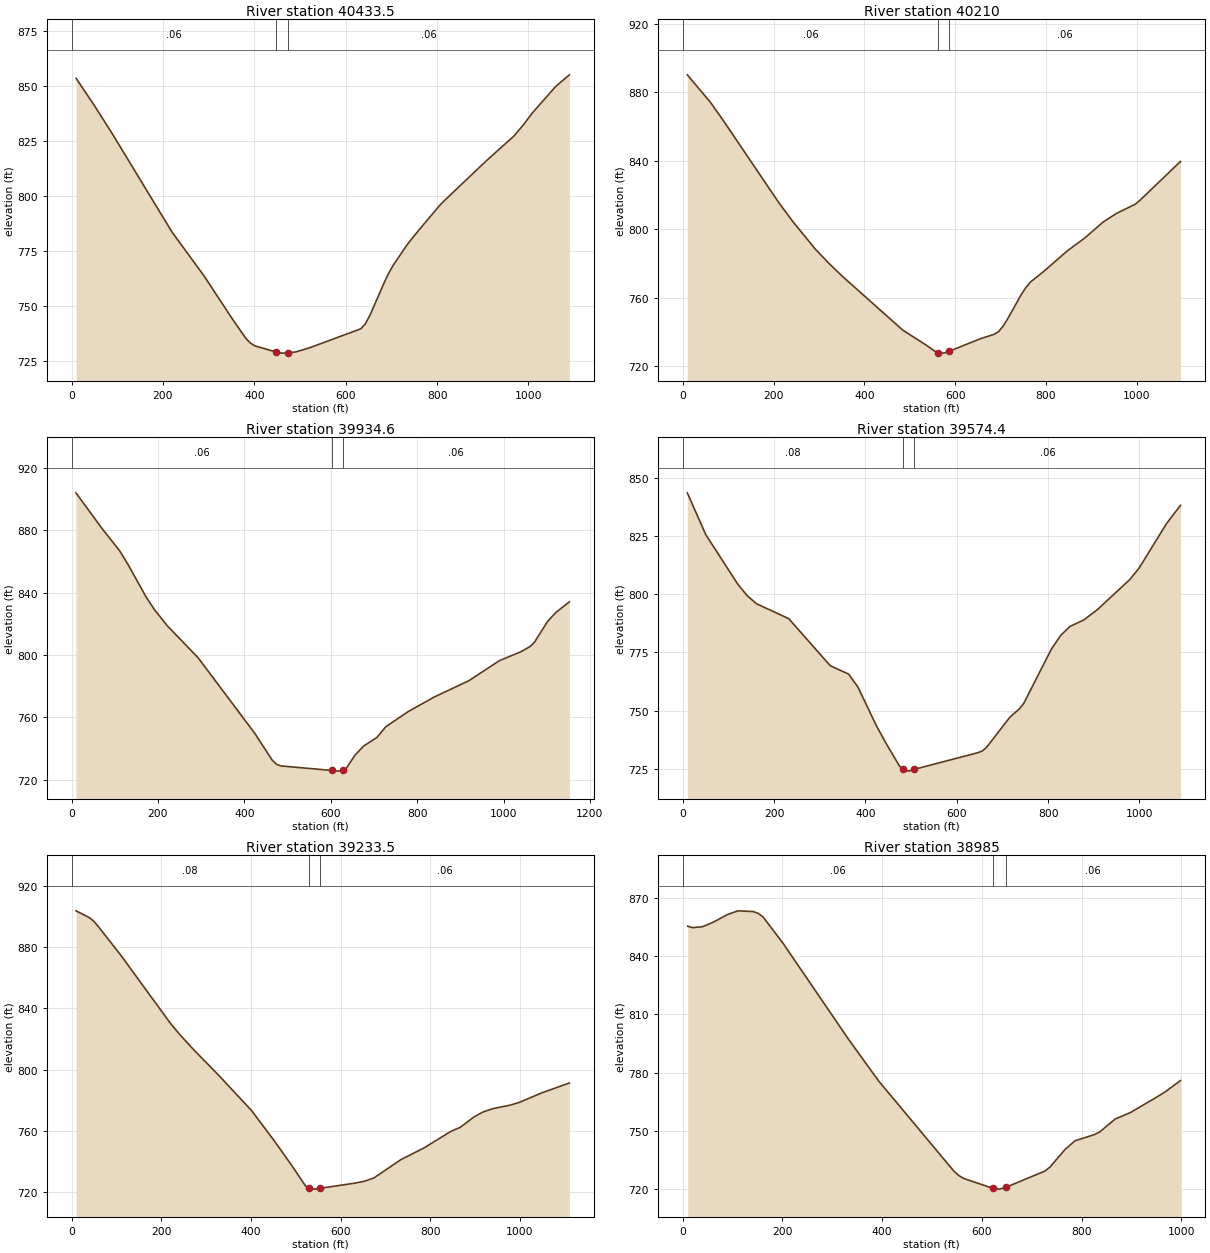
Type RM Length L Ch R = 1 ,40433.5 ,231.3,223.5,218
XS GIS Cut Line= 3
     1525045.891      416390.717     1525264.997      416795.788
     1525523.368      417369.238
#Sta/Elev= 30
      10   853.6    50.1   841.2    90.1  828.12   220.3  783.63   290.3  763.76
   350.4  744.76   380.4  735.77   390.5  733.47   400.5  732.11     448  729.23
   460.5  728.75     473  728.81     491  729.32   521.4   731.2     633  739.81
   643.1   742.1   653.3  746.08   683.7  760.52   693.9  764.99     704  768.69
   734.4  778.01   754.7  783.31   805.4  795.82   815.6  797.98   906.9  815.99
   967.8  827.33   988.1   832.3  1008.3  837.84  1059.1  849.83  1089.5  855.21
#Mann= 3 , 0 , 0
       0     .06       0     448    .045       0     473     .06       0
Bank Sta=448,473
XS Rating Curve= 0 ,0
Exp/Cntr=0.3,0.1

Type RM Length L Ch R = 1 ,40210   ,269.5,275.4,280.6
XS GIS Cut Line= 4
     1524850.411      416479.419     1525087.957      416901.723
     1525237.523      417064.487     1525466.272      417381.215
#Sta/Elev= 30
    10.1  890.22    60.6  874.33    90.8  862.97     212   815.4   242.3  804.56
   292.7  788.19     323   779.8   353.3  772.11   484.5  741.07   534.8  732.55
   554.9  728.78   562.5   727.9     575  727.61   587.5  728.77   655.3     736
   685.5  738.57   695.5  740.16   705.6  743.39   715.6  747.66   745.6  761.83
   755.7  765.89   765.7  769.13   795.7  775.49   845.8   787.1   885.9  794.98
     926  804.25     956  809.35   996.1  814.55  1006.1   816.7  1096.3  839.62
#Mann= 3 , 0 , 0
       0     .06       0   562.5    .045       0   587.5     .06       0
Bank Sta=562.5,587.5
XS Rating Curve= 0 ,0
Exp/Cntr=0.3,0.1

Type RM Length L Ch R = 1 ,39934.6 ,340.8,360.2,362.9
XS GIS Cut Line= 3
     1524685.534      416562.313     1524917.014      417078.062
      1525198.56      417593.285
#Sta/Elev= 30
    10.1  903.94    70.7     881     111  866.91   131.2  857.79   171.6  837.66
   191.8  829.08   222.1  818.59   292.8  798.29     424  749.85   464.4  732.64
   474.5  729.94   484.6  728.91   603.4  725.98   615.9  725.57   628.4  726.14
   636.2  727.46   656.4  735.89   676.7  741.78     707  747.17   727.3  753.99
   777.9  763.48   838.6  772.95   919.6   783.5   990.5  796.38  1041.1  802.21
  1061.3  805.42  1071.5  808.14  1101.8  821.49  1122.1  827.48  1152.4   834.1
#Mann= 3 , 0 , 0
       0     .06       0   603.4    .045       0   628.4     .06       0
Bank Sta=603.4,628.4
XS Rating Curve= 0 ,0
Exp/Cntr=0.3,0.1

Type RM Length L Ch R = 1 ,39574.4 ,343.3,340.9,340.5
XS GIS Cut Line= 2
     1524458.899      416690.571     1524933.992       417671.55
#Sta/Elev= 30
    10.1   843.5    50.5  825.55   121.1  804.13   141.3  799.32   161.5  795.88
   232.1  789.48     323  769.27   363.3  765.65   383.5  760.15   423.9  743.57
   444.1  736.32   474.3   726.3     482  724.81   494.5  723.99     507  724.76
   645.9  731.88     656  732.64   666.1  734.39   716.6  747.22   736.7  750.63
   746.8  753.12   807.4  776.43   827.6  782.28   847.8   786.1     878  788.87
   908.3   793.4     979  806.28   999.1  811.13  1059.7  830.39    1090  838.15
#Mann= 3 , 0 , 0
       0     .08       0     482    .045       0     507     .06       0
Bank Sta=482,507
XS Rating Curve= 0 ,0
Exp/Cntr=0.3,0.1

Type RM Length L Ch R = 1 ,39233.5 ,259.8,248.5,235.8
XS GIS Cut Line= 3
     1524090.157      416811.819     1524362.088      417269.112
     1524621.662      417785.924
#Sta/Elev= 30
      10  903.58    40.2  899.08    50.2  896.59    60.2  893.16   110.4  874.42
   220.8  830.11   240.9  823.06     271  813.46   331.3  795.35   401.5  773.32
   451.7  753.79   491.9   737.2     522  724.08   529.7  722.63   542.2  722.08
   554.7  722.62   633.5  726.06   653.8  727.29   674.1  729.34     735  741.38
   785.7  748.88   846.6  759.84   866.9  762.36   897.3  769.09   917.6  772.36
   937.9  774.44   978.5  776.88   998.8  778.66  1049.5  784.95  1110.4   791.3
#Mann= 3 , 0 , 0
       0     .08       0   529.7    .045       0   554.7     .06       0
Bank Sta=529.7,554.7
XS Rating Curve= 0 ,0
Exp/Cntr=0.3,0.1

Type RM Length L Ch R = 1 ,38985   ,279.1,296.8,312.3
XS GIS Cut Line= 4
      1523878.23      416994.103     1524203.757      417442.801
     1524348.924      417552.776     1524546.879      417724.338
#Sta/Elev= 30
    10.1  855.43    20.2   854.7    40.3  855.22    60.5  857.41    90.7  861.57
   110.9  863.37   141.1  863.01   151.2  862.11   161.3  860.21   201.6  846.51
   332.6  797.18   393.1  775.66   534.2  732.22   544.3  729.17   554.3  726.85
   564.5  725.39   622.8  720.34   635.3  719.97   647.8  720.87   726.3  729.27
   736.5  731.32   766.7  740.37   786.8  744.89   827.1   748.2   837.2  749.61
   867.4   756.1   897.7  759.41     948  766.98   968.2   770.2   998.4  775.93
#Mann= 3 , 0 , 0
       0     .06       0   622.8    .045       0   647.8     .06       0
Bank Sta=622.8,647.8
XS Rating Curve= 0 ,0
Exp/Cntr=0.3,0.1

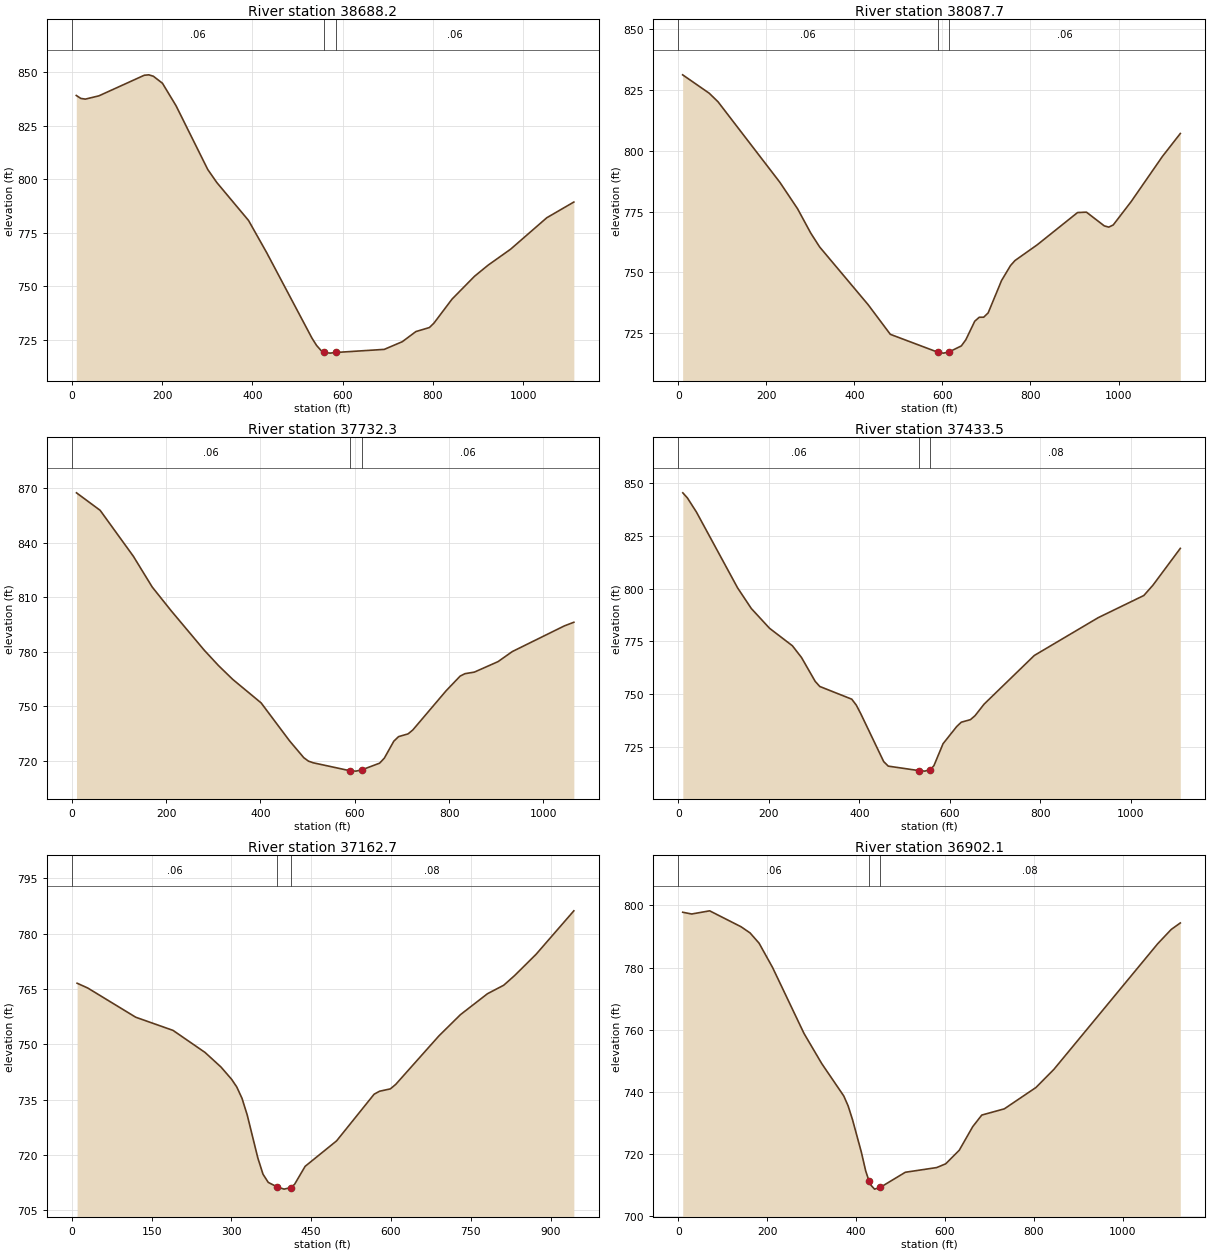
Type RM Length L Ch R = 1 ,38688.2 ,576.6,600.5,625
XS GIS Cut Line= 3
     1523838.321      417040.911     1524015.267      417574.777
     1524165.847      418103.725
#Sta/Elev= 30
      10   839.1    20.1  837.72    30.1   837.4    60.3  838.94   160.7  848.54
   170.7  848.73   180.8  848.07   200.9   844.8     231  834.33   301.3  804.57
   321.4  798.49   391.7  780.79   431.9  765.76   532.3  725.87   542.3  722.53
   552.4  720.13   559.9  719.29   572.4  718.92   584.9  719.22   692.4  720.67
   732.4  724.26   762.4  728.97   792.4  730.86   802.4   732.9   842.4  744.08
   892.4  754.78   922.4  759.94   972.4  767.41  1052.4  782.06  1112.4  789.39
#Mann= 3 , 0 , 0
       0     .06       0   559.9    .045       0   584.9     .06       0
Bank Sta=559.9,584.9
XS Rating Curve= 0 ,0
Exp/Cntr=0.3,0.1

Type RM Length L Ch R = 1 ,38087.7 ,350.2,355.5,359.3
XS GIS Cut Line= 3
     1523772.654      417082.083     1523496.475      417594.463
     1523177.102      418052.285
#Sta/Elev= 30
      10   831.2    70.3  823.64    90.3  820.13   230.8  787.01     271  776.14
   301.1  766.09   321.1  760.44   431.5  736.64   481.7   724.5   589.9  717.12
   602.4  716.77   614.9  717.24     643  719.74   653.1  722.24   673.4  729.88
   683.6  731.51   693.7  731.54   703.9  733.31   734.3  746.62   754.6  752.76
   764.8  754.84   815.5  761.33   906.9  774.57   927.1  774.73   967.7  769.08
   977.9  768.58     988  769.48  1028.6  779.06  1099.7  797.65  1140.3  807.07
#Mann= 3 , 0 , 0
       0     .06       0   589.9    .045       0   614.9     .06       0
Bank Sta=589.9,614.9
XS Rating Curve= 0 ,0
Exp/Cntr=0.3,0.1

Type RM Length L Ch R = 1 ,37732.3 ,295.7,298.8,300.8
XS GIS Cut Line= 4
     1523592.445      416990.681     1523292.982      417328.784
     1523041.819      417575.116     1522877.598      417777.978
#Sta/Elev= 30
      10  867.37    60.2  857.73   130.5   832.5   170.6  815.53   210.8  802.47
     281  780.75   311.1  772.32   341.2  764.74   401.5  751.78   461.7  730.93
   491.9  721.64   501.9  719.74     512  718.83   589.9  714.46   602.4  714.25
   614.9  714.95   652.7  718.63   662.7   721.4   682.8  730.72   692.9  733.23
     713  734.74     723  736.87   793.4  758.38   823.5  766.55   833.6  767.86
   853.6  768.73   903.8   774.5     934  780.03  1044.4  794.16  1064.5  796.15
#Mann= 3 , 0 , 0
       0     .06       0   589.9    .045       0   614.9     .06       0
Bank Sta=589.9,614.9
XS Rating Curve= 0 ,0
Exp/Cntr=0.3,0.1

Type RM Length L Ch R = 1 ,37433.5 ,279.8,270.8,262.8
XS GIS Cut Line= 3
     1523427.709      416879.631     1522990.565      417221.231
     1522567.326       417579.17
#Sta/Elev= 30
    10.1  845.53    20.2  843.12    40.3  836.37   131.1  800.44   161.4  790.65
   201.7  781.26   252.2  772.96   272.3  767.39   302.6  756.05   312.7  753.64
   383.3  747.62   393.4  744.79   403.5   740.6   453.9  717.99     464  715.85
   532.2  713.71   544.7  713.48   557.2  714.23   564.9  716.11     585  726.49
   615.3  734.68   625.3   736.7   645.5  737.91   655.6  739.78   675.7  745.27
   786.6  768.36   927.7  786.29  1028.5  796.81  1048.6  801.69  1109.1  819.18
#Mann= 3 , 0 , 0
       0     .06       0   532.2    .045       0   557.2     .08       0
Bank Sta=532.2,557.2
XS Rating Curve= 0 ,0
Exp/Cntr=0.3,0.1

Type RM Length L Ch R = 1 ,37162.7 ,271.7,260.6,249.5
XS GIS Cut Line= 4
      1523128.76      416696.048     1522921.068       416884.42
     1522790.657      417082.452     1522558.815      417439.875
#Sta/Elev= 30
      10  766.57      30  765.27   120.2  757.34   190.3  753.77   250.4  747.79
   280.4  743.83   300.2  740.53     310  738.44   319.9  735.34   329.8  730.77
   349.6  719.18   359.4  714.74   369.3  712.52   386.4  711.27     399   710.7
   411.4  711.12   418.7     712   438.5  716.88   497.7   723.8   568.2  736.46
   578.4  737.26   598.7   737.9   608.8  739.12   689.9  752.27   730.5  758.05
   781.2  763.72   811.7  766.02     832  768.62   872.5  774.41   943.5  786.21
#Mann= 3 , 0 , 0
       0     .06       0   386.4    .045       0   411.4     .08       0
Bank Sta=386.4,411.4
XS Rating Curve= 0 ,0
Exp/Cntr=0.3,0.1

Type RM Length L Ch R = 1 ,36902.1 ,463.5,437.3,410.3
XS GIS Cut Line= 4
     1522782.878      416453.025     1522652.357      416726.538
     1522611.032      416950.181     1522448.553      417526.382
#Sta/Elev= 30
    10.1  797.79    30.3  797.23    70.7  798.25   141.4  793.12   161.6  791.14
   181.8  787.85   212.1  780.05   282.9  758.82   322.8  749.13   372.3  738.73
   382.2   735.5   392.1  731.04   411.8  720.69   421.7  714.58     429  711.44
   431.6  710.33   441.5  708.78     454  709.31   510.7   714.2   581.2  715.71
   601.5  716.91     632  721.28   662.4  728.88   682.7  732.59   733.4  734.59
   804.5  741.45     845   747.3  1078.4  787.68  1108.9  792.28  1129.2  794.35
#Mann= 3 , 0 , 0
       0     .06       0     429    .045       0     454     .08       0
Bank Sta=429,454
XS Rating Curve= 0 ,0
Exp/Cntr=0.3,0.1

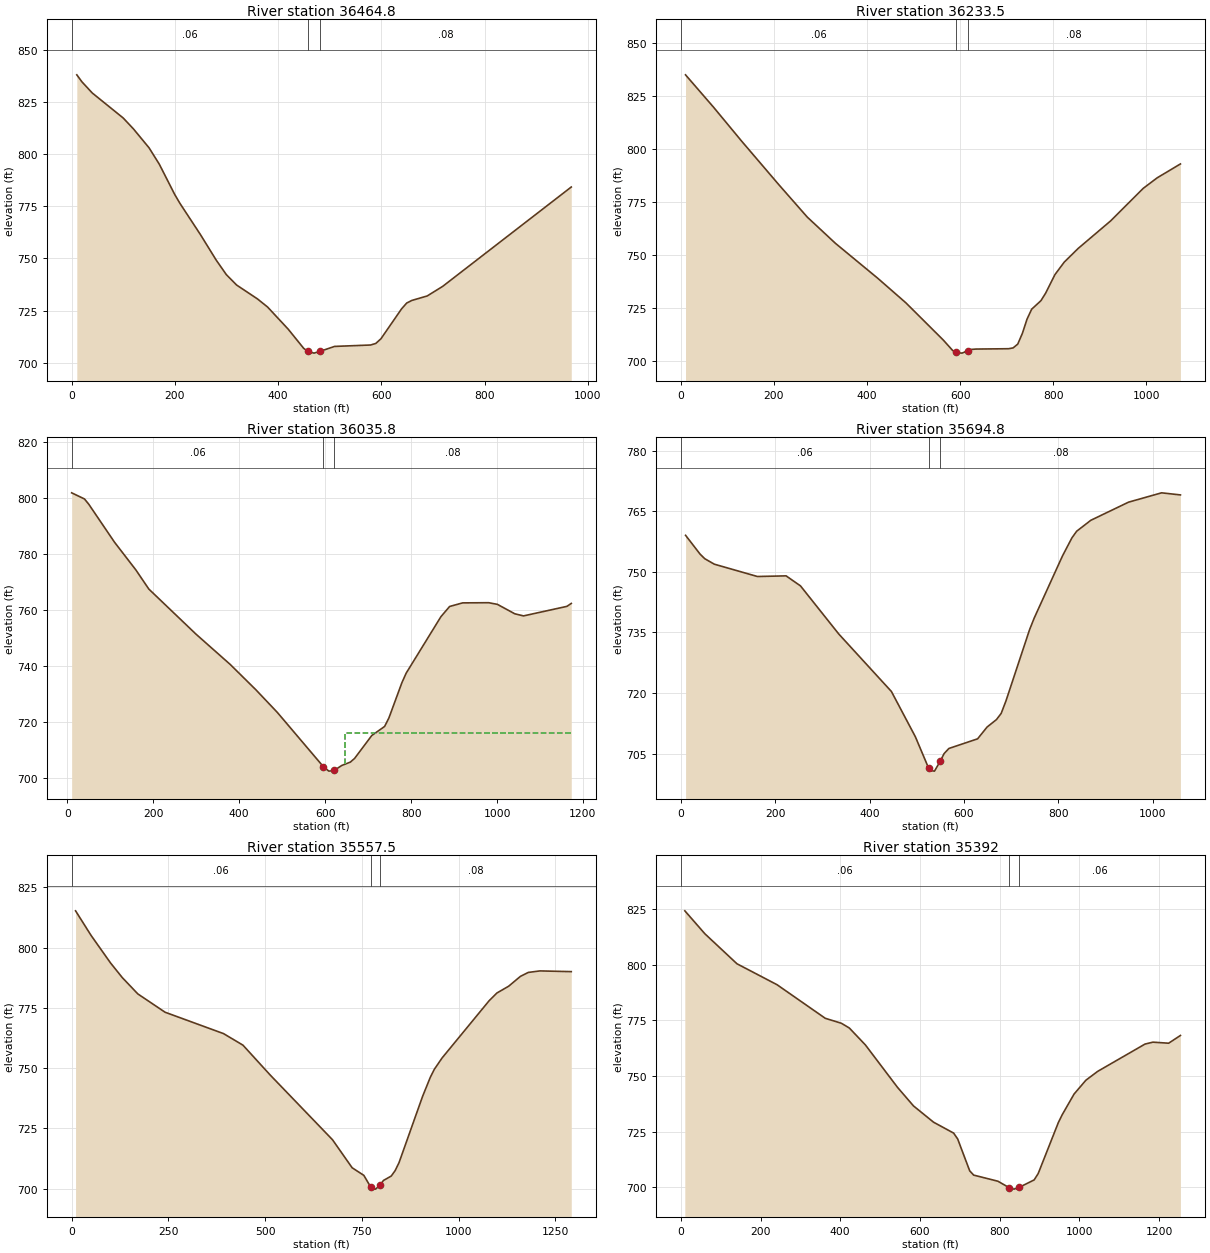
Type RM Length L Ch R = 1 ,36464.8 ,226,231.3,236.8
XS GIS Cut Line= 4
      1522080.64      416623.597     1522259.352      416981.021
     1522438.064      417154.902     1522433.234      417473.685
#Sta/Elev= 30
      10  837.94      20  834.57      40  829.23    99.9  817.26   119.9  811.99
   149.9  803.01   169.8  795.15   199.8  780.58   209.8  776.38   249.8  761.32
   279.7  749.35   299.7  742.25   319.7  737.26   359.7  730.69   379.6  726.75
   419.6  716.12   449.5  706.97   456.9  705.64   469.4  704.68   481.9   705.6
   509.3  707.89   579.1  708.57   589.1  709.31   599.1  711.54     639  725.85
     649  728.65   658.9   729.9   688.8  732.06   718.7  736.64   967.8  784.22
#Mann= 3 , 0 , 0
       0     .06       0   456.9    .045       0   481.9     .08       0
Bank Sta=456.9,481.9
XS Rating Curve= 0 ,0
Exp/Cntr=0.3,0.1

Type RM Length L Ch R = 1 ,36233.5 ,181.3,197.7,214.8
XS GIS Cut Line= 3
     1521814.743      416676.884     1522138.354      417174.853
     1522408.962      417570.372
#Sta/Elev= 30
    10.1  835.15    70.5  819.79   130.9  803.74   211.4     783   271.8  767.87
   332.2  755.49   422.8  739.03   483.2  727.43   563.7   709.8   583.8  704.88
   591.4  703.96   603.9  703.61   616.4  704.69   623.8  705.36   633.8  705.53
   703.7  705.69   713.7  706.07   723.7  707.88   733.7  712.99   743.6  719.67
   753.6  724.37   773.6  728.43   783.6  731.97   803.5   740.7   823.5  746.62
   853.5   753.1   923.4  766.15   993.2  781.49  1023.2  786.47  1073.1  793.03
#Mann= 3 , 0 , 0
       0     .06       0   591.4    .045       0   616.4     .08       0
Bank Sta=591.4,616.4
XS Rating Curve= 0 ,0
Exp/Cntr=0.3,0.1

Type RM Length L Ch R = 1 ,36035.8 ,388.5,340.9,292.4
XS GIS Cut Line= 4
     1521687.525      416743.359     1521964.663      417170.063
     1521960.264      417429.604     1522246.199       417715.54
#Sta/Elev= 30
      10  801.85    39.9  799.65    49.9  797.76   109.7   784.2   159.6  774.24
   189.6  767.43   299.3  751.31   379.1  740.45     439  731.36   488.9  723.26
   596.1  703.84   608.6  702.29   621.1  702.54   638.6  704.31   658.6  705.51
   668.5  706.83   708.5  715.03   738.4  718.27   748.4  721.32   778.5  733.88
   788.6  737.35   869.5  757.55   889.7  761.19     920  762.48   980.7  762.54
  1000.9  761.95  1041.3  758.58  1061.6  757.82  1162.6  761.23  1172.8  762.28
#Mann= 3 , 0 , 0
      10     .06       0   596.1    .045       0   621.1     .08       0
#XS Ineff= 2 , 0
                          647.25           715.8
Permanent Ineff=
       F       F
Bank Sta=596.1,621.1
XS Rating Curve= 0 ,0
Exp/Cntr=0.3,0.1

Type RM Length L Ch R = 1 ,35694.8 ,119.6,137.3,155.1
XS GIS Cut Line= 4
     1521627.904      416956.302     1521676.518      417399.903
      1521858.82       417387.75     1522153.541      417700.701
#Sta/Elev= 30
    10.1  759.06    40.6  754.44    50.7  753.27      71  751.91   162.3  748.86
   223.1  749.02   253.6  746.54   334.7  734.63   446.3  720.39     497   709.2
   525.1  701.42   527.5  700.84   537.6  700.67   550.1   703.2   557.9     705
   568.1  706.28     629  708.67     649  711.58     669  713.44   678.9  714.96
   688.9     718   738.9  735.63   748.9  738.57   808.9  753.97   828.9  758.44
   838.9  760.07   868.9  762.78   948.9  767.27  1018.9  769.58  1058.8  769.06
#Mann= 3 , 0 , 0
       0     .06       0   525.1    .045       0   550.1     .08       0
Bank Sta=525.1,550.1
XS Rating Curve= 0 ,0
Exp/Cntr=0.3,0.1

Type RM Length L Ch R = 1 ,35557.5 ,156.9,165.5,174.7
XS GIS Cut Line= 3
     1521544.338      416790.107     1521625.305      417459.354
     1522147.595      417787.459
#Sta/Elev= 30
    10.1  815.21    50.3  804.99   100.6  793.57   130.8  787.53     171  780.75
   241.5  773.15   392.4  764.29   442.7  759.49   513.1   747.1   674.1  720.25
   724.7  708.66     755  705.49   772.9   700.6   785.4  699.79   797.9  701.65
   805.6  703.38   825.8  705.22   835.9  707.48     846  710.82   906.7  738.24
   926.9  746.24     937  749.46   957.2   754.2  1078.6  777.91  1098.8  781.13
  1129.1  783.94  1159.5  788.02  1179.7  789.66    1210  790.29  1290.9  789.99
#Mann= 3 , 0 , 0
       0     .06       0   772.9    .045       0   797.9     .08       0
Bank Sta=772.9,797.9
XS Rating Curve= 0 ,0
Exp/Cntr=0.3,0.1

Type RM Length L Ch R = 1 ,35392   ,318.4,360.6,402.1
XS GIS Cut Line= 4
     1521507.166      416804.945     1521524.762      417539.579
     1521661.131      417702.343     1521771.106      417988.278
#Sta/Elev= 30
    10.1  824.11    60.4  813.81   140.9  800.35   241.6  790.94   362.4  775.89
   402.7  773.67   422.8  771.53   463.1  763.94   543.6  744.92   583.8  736.57
   634.2  729.26   684.5  724.38   694.6  721.76   724.8  707.45   734.8  705.53
   795.5  702.79   823.5  699.93     836  699.24   848.5     700   886.5  703.37
   896.6  706.21   947.2  729.11   957.1  732.69   986.7  741.91  1016.4  748.12
    1046  752.09  1164.6  764.32  1184.4  765.18  1223.9  764.71  1253.5  768.19
#Mann= 3 , 0 , 0
       0     .06       0   823.5    .045       0   848.5     .06       0
Bank Sta=823.5,848.5
XS Rating Curve= 0 ,0
Exp/Cntr=0.3,0.1

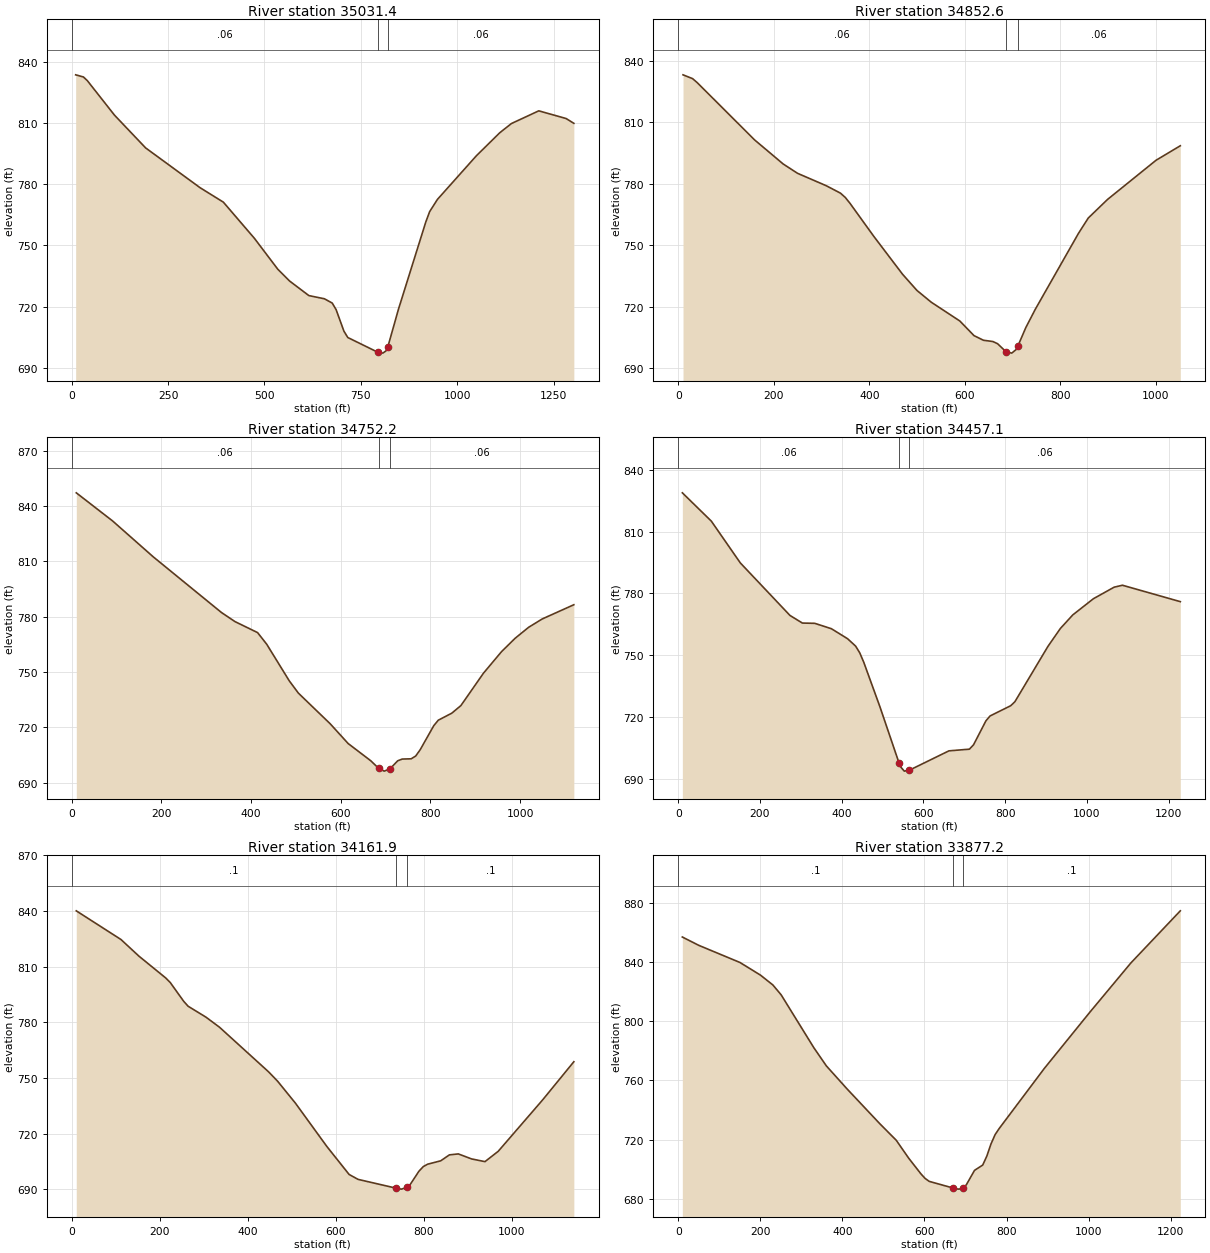
Type RM Length L Ch R = 1 ,35031.4 ,171.4,178.8,186.3
XS GIS Cut Line= 3
     1521444.261      416793.268     1521427.984      417438.402
     1520949.374      417888.906
#Sta/Elev= 30
    10.1  833.54    30.3  832.49    40.3  830.71   110.9  813.79   191.6  797.77
   332.8   778.3   393.3  771.21   473.9   753.5   534.4  738.41   564.7  732.67
   615.1  725.48   655.5  723.91   675.7  721.82   685.8  718.61     706   708.1
   716.1  704.96   794.6  697.69   807.1  697.31   817.2   698.7   819.6   700.1
   847.6  718.81   918.4  761.45   928.5  766.58   948.7  772.56  1049.8  793.93
  1110.5   805.2  1140.8  809.71  1211.6  815.91  1282.4  812.16  1302.6   809.8
#Mann= 3 , 0 , 0
       0     .06       0   794.6    .045       0   819.6     .06       0
Bank Sta=794.6,819.6
XS Rating Curve= 0 ,0
Exp/Cntr=0.3,0.1

Type RM Length L Ch R = 1 ,34852.6 ,101.6,100.4,99.3
XS GIS Cut Line= 4
     1521427.372      416795.268     1521281.531      417366.481
     1521117.459      417457.632     1520941.234      417667.279
#Sta/Elev= 30
      10  833.29      30  831.44      40  829.42   159.9  801.47   219.8  789.69
   249.8  785.14   309.8  779.09   339.7  775.44   349.7  773.35   359.7  770.44
   409.7  754.24   469.6  735.81   499.6  727.92   529.6  722.15   589.5  712.95
   619.2   705.8   638.9  703.54   658.7  702.91   668.6  701.84   685.7  698.03
   698.2  697.24   708.1  699.13   710.7  700.51   727.8  709.79   747.6  718.71
   838.1  755.86   858.4  763.28   898.9   772.4  1000.4  791.54  1051.1  798.61
#Mann= 3 , 0 , 0
       0     .06       0   685.7    .045       0   710.7     .06       0
Bank Sta=685.7,710.7
XS Rating Curve= 0 ,0
Exp/Cntr=0.3,0.1

Type RM Length L Ch R = 1 ,34752.2 ,327.9,295.1,262.4
XS GIS Cut Line= 4
     1521324.812      416693.385     1521254.428      417265.255
      1521065.27       417379.63     1520883.505      417646.011
#Sta/Elev= 30
    10.1  847.12      91  831.88     182  812.35   333.6  782.26   363.9   777.3
   414.4  771.32   434.7  765.04   485.2  745.11   505.4   738.5   576.2  721.91
   616.4  711.16   666.6  701.86   684.3  697.76   696.8   696.2   709.3  697.35
   726.9   701.8   736.9  702.74     757  702.88   767.1  704.42   777.1  707.83
   807.3  720.84   817.4  723.82   847.6  727.64   867.8  731.74   918.2  749.33
   958.5  761.01   988.7  768.23  1018.9   774.2  1049.2  778.72  1119.7  786.43
#Mann= 3 , 0 , 0
       0     .06       0   684.3    .045       0   709.3     .06       0
Bank Sta=684.3,709.3
XS Rating Curve= 0 ,0
Exp/Cntr=0.3,0.1

Type RM Length L Ch R = 1 ,34457.1 ,293.1,295.2,297.2
XS GIS Cut Line= 4
     1521051.182      416644.053     1520917.699      416994.103
     1520966.088      417297.634     1520793.724      417816.157
#Sta/Elev= 30
    10.1   828.8      81  815.06   151.9   794.8   273.4  769.31   303.8  765.62
   334.1  765.49   374.6  762.89   414.3  758.03   434.1  754.41     444  751.22
     454  746.57   493.6  724.94   540.6  697.52   543.2  696.06   553.1  693.79
   565.6  694.25   662.2  703.62   712.4  704.44   722.5  706.56   752.8  718.19
     763  720.56   813.5  725.53   823.7  727.46   904.6  754.32     935     763
   965.3  769.57  1015.9  777.44  1066.5  783.03  1086.8  783.97  1228.4  776.01
#Mann= 3 , 0 , 0
       0     .06       0   540.6    .045       0   565.6     .06       0
Bank Sta=540.6,565.6
XS Rating Curve= 0 ,0
Exp/Cntr=0.3,0.1

Type RM Length L Ch R = 1 ,34161.9 ,249.4,284.7,320.1
XS GIS Cut Line= 4
     1520996.881      416624.586     1520671.355      417187.659
     1520688.951      417394.412     1520587.773      417658.353
#Sta/Elev= 30
    10.2  840.11   111.8  824.64   152.4  815.71   213.4  803.92   223.6  801.49
   254.1  791.38   264.2  788.68   304.9  782.77   335.4  777.39   447.1   753.3
   467.5  748.27   508.1   736.4   579.3  713.11   630.1  697.94   650.4   695.3
   736.7  690.56   749.2  690.04   761.7  691.06     769  692.59   788.7   699.7
   798.6   702.2   808.5  703.49   838.1   705.3   857.9  708.51   878.1  709.03
   908.4  706.32   938.7  704.86   968.9  710.46  1069.9  738.21  1140.6  758.74
#Mann= 3 , 0 , 0
       0      .1       0   736.7    .045       0   761.7      .1       0
Bank Sta=736.7,761.7
XS Rating Curve= 0 ,0
Exp/Cntr=0.3,0.1

Type RM Length L Ch R = 1 ,33877.2 ,298.7,291,282.9
XS GIS Cut Line= 3
     1520941.515      416577.101     1520662.557      417029.295
     1520019.764      417285.488
#Sta/Elev= 30
      10  856.74    50.1  851.12   150.4  839.57   200.5  831.02   230.6  824.39
   250.6  817.81   330.8  781.91   360.9  769.82     411  754.39   491.2  730.79
   531.3  719.62   561.4   707.6   591.5  696.93   601.5  693.92   611.5  691.92
   669.2  687.47   681.7  686.69   691.8  687.01   694.2  687.62   701.8  689.55
   721.9  699.35   741.9  702.93   751.9  708.99     762  717.16     772  723.42
     782  727.58   892.3  768.22  1002.7  805.96  1102.9  839.26  1223.3  874.41
#Mann= 3 , 0 , 0
       0      .1       0   669.2    .045       0   694.2      .1       0
Bank Sta=669.2,694.2
XS Rating Curve= 0 ,0
Exp/Cntr=0.3,0.1

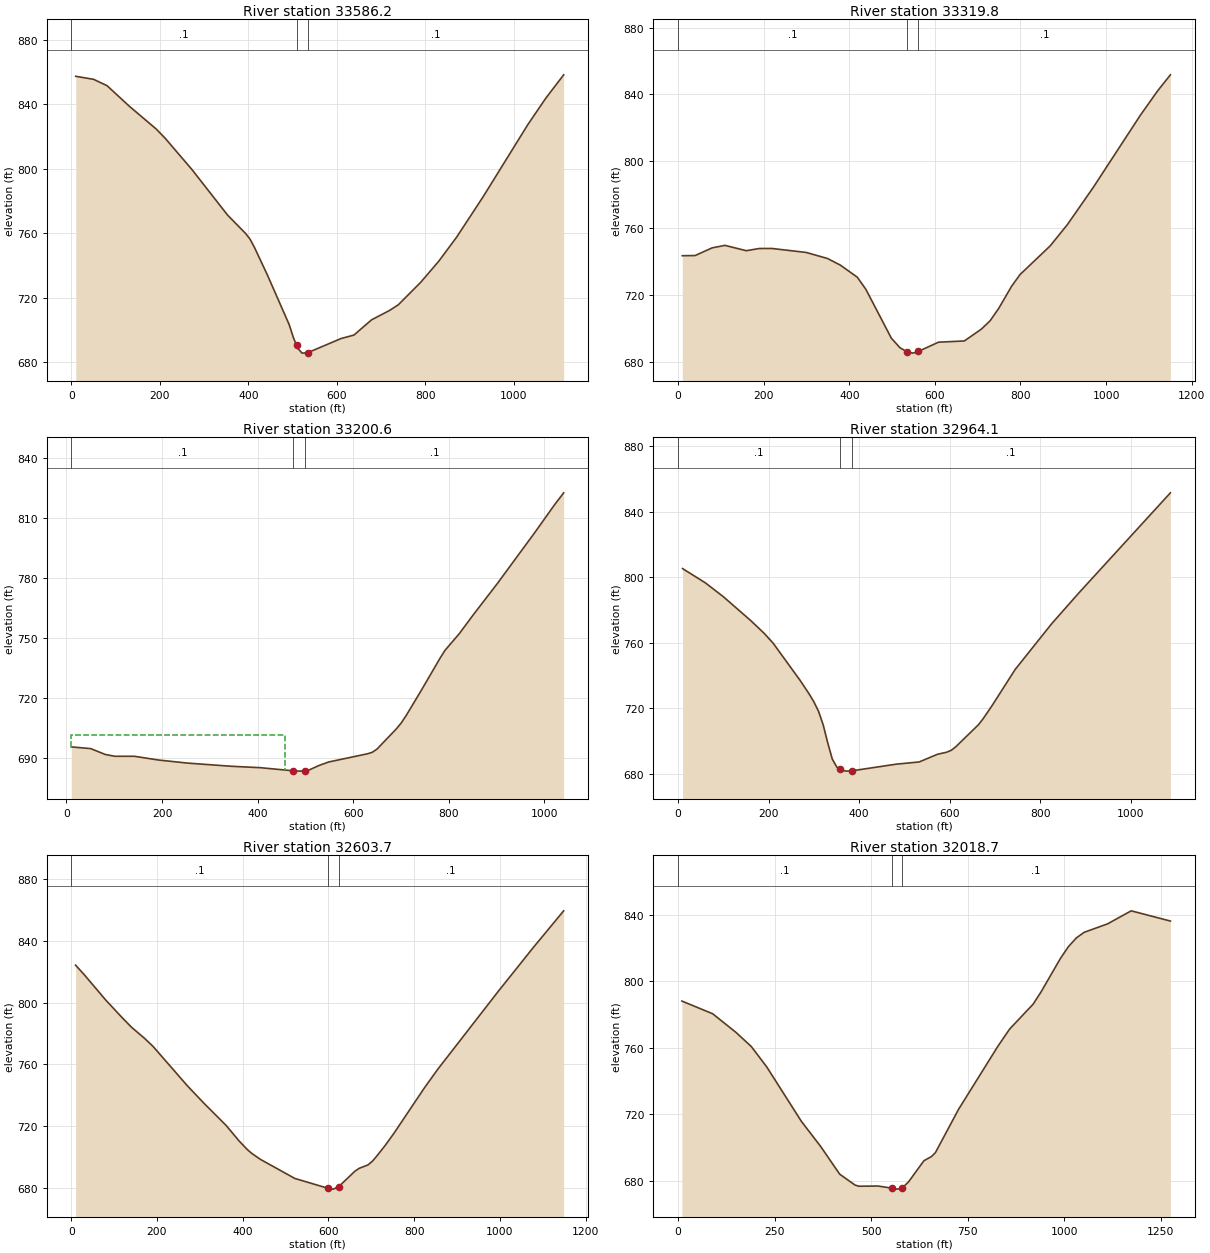
Type RM Length L Ch R = 1 ,33586.2 ,275.5,266.4,257.5
XS GIS Cut Line= 4
     1520815.168      416430.395     1520539.855      416739.518
     1520346.654       416889.25      1520023.04      417208.033
#Sta/Elev= 30
    10.1  857.53    50.5  855.64    80.8   851.7   131.3  838.88   191.8  824.78
     212  819.06   272.6  799.57   353.4  771.17   393.8  759.85   403.9  756.29
   413.9  751.16   443.3  733.92   492.2  703.28   501.9  695.09     509  690.28
   511.7  688.45   521.5  685.43     534  685.67   609.5  694.49   638.8  696.68
   678.6  706.15   718.9  711.91   739.1  715.52   789.6  729.47     830  742.45
   870.4  757.39   930.9  782.76  1031.9   827.6  1072.3  843.95  1112.6  858.44
#Mann= 3 , 0 , 0
       0      .1       0     509    .045       0     534      .1       0
Bank Sta=509,534
XS Rating Curve= 0 ,0
Exp/Cntr=0.3,0.1

Type RM Length L Ch R = 1 ,33319.8 ,122.4,119.2,135.9
XS GIS Cut Line= 3
     1520562.063      416170.194     1520281.429       416594.11
     1519929.508      417130.789
#Sta/Elev= 30
      10  743.45    39.9  743.55    79.7  748.15   109.7  749.65   159.5  746.45
   189.4  747.76   219.3  747.79   299.1  745.42   348.9  741.82   378.8  737.88
   418.7  730.62   438.6  723.43   498.4  694.05   518.4  688.39     536  685.74
   548.5  685.13     561  686.13   608.7  691.69   668.8  692.41   708.9  699.55
     729   704.5   749.1  711.88   779.1  725.11   799.2  732.24   869.4  749.35
   909.5  762.05   969.7  784.23    1080  827.54  1120.1  842.06  1150.2  851.75
#Mann= 3 , 0 , 0
       0      .1       0     536    .045       0     561      .1       0
Bank Sta=536,561
XS Rating Curve= 0 ,0
Exp/Cntr=0.3,0.1

Type RM Length L Ch R = 1 ,33200.6 ,257.1,236.5,216.9
XS GIS Cut Line= 3
      1520391.29      416117.713     1520029.724      416822.614
     1519902.113      417035.299
#Sta/Elev= 30
    10.2  695.69    50.8  694.83    81.3  691.91   101.6  690.99   142.2     691
     193  689.12   253.9  687.59   345.3  686.01   406.3   685.3     475  683.74
   487.5  683.59     500  683.75   507.8  684.16   528.1  686.38   548.5  688.14
   629.7  692.24   639.9  692.98     650  694.64   690.7   704.8   700.8  707.74
     711  711.42   741.4  723.49   782.1  740.13   792.2  743.93     822  752.24
   851.7  761.78   901.4  777.19   980.7  802.96  1020.4  816.29  1040.3  822.52
#Mann= 3 , 0 , 0
    10.2      .1       0     475    .045       0     500      .1       0
#XS Ineff= 2 , 0
          457.03  701.52
Permanent Ineff=
       F       F
Bank Sta=475,500
XS Rating Curve= 0 ,0
Exp/Cntr=0.3,0.1

Type RM Length L Ch R = 1 ,32964.1 ,360.5,360.4,360.4
XS GIS Cut Line= 4
     1519976.312      416070.311     1519945.519      416338.651
      1519985.11      416628.985     1519831.144      417130.472
#Sta/Elev= 30
      10  805.36      60  796.73     100  788.21   160.1  773.73   190.1  765.87
   210.1   759.8   270.1  736.91   290.3  728.51   300.4  723.81   310.5   718.1
   320.6     710   330.7  698.94   340.8  688.99   350.9  684.02   358.6  682.65
   371.1  681.62   383.6  681.78   482.3  685.88   532.8  687.23   573.2  691.92
   593.4  693.16   603.5  694.33   613.6  696.49     664  710.06   674.1  713.66
   694.3  721.87   744.7   743.7   825.4  771.66   885.9  790.61  1087.7  851.64
#Mann= 3 , 0 , 0
       0      .1       0   358.6    .045       0   383.6      .1       0
Bank Sta=358.6,383.6
XS Rating Curve= 0 ,0
Exp/Cntr=0.3,0.1

Type RM Length L Ch R = 1 ,32603.7 ,576.6,585,598.1
XS GIS Cut Line= 3
     1519531.164      416033.297     1519690.376      416686.172
     1519763.553      417157.484
#Sta/Elev= 30
      10  824.33    30.1  818.19    80.2  801.78   120.4  789.78   140.4  784.13
   170.5  776.99   190.6  771.72   270.8  746.17   310.9  734.44   361.1  720.52
   391.2  710.51   411.2  704.69   421.3  702.29   441.3  698.45   521.6  686.09
   599.3  679.68   611.8  679.16   624.3  680.81     662  690.82     672  692.66
   692.3  694.84   702.5  697.21   712.6  700.47   732.9  707.63   753.2  715.44
   824.2  744.85   854.7  756.65   996.7  807.45  1077.9  835.66    1149  859.52
#Mann= 3 , 0 , 0
       0      .1       0   599.3    .045       0   624.3      .1       0
Bank Sta=599.3,624.3
XS Rating Curve= 0 ,0
Exp/Cntr=0.3,0.1

Type RM Length L Ch R = 1 ,32018.7 ,248.1,239.8,231.6
XS GIS Cut Line= 4
     1519121.405      416061.178     1519210.884      416378.242
     1519166.894      416752.157     1519506.613      417208.341
#Sta/Elev= 30
      10  788.14    89.8   780.5   149.7  769.37   189.7  760.81   229.6  748.59
   319.5  715.78   369.1  700.79   418.6  684.05   458.2  677.53   468.2  676.81
   517.7  676.94   554.7  675.61   567.2  675.07   579.7  675.62     597  679.49
   636.6  692.14   656.4   694.7   666.3     697   726.3  723.06   827.8  760.86
   858.3  771.26   919.2  786.25   939.5  793.51   990.3  813.87  1010.6  820.83
    1031  826.05  1051.3  829.46  1112.2  834.57  1173.2  842.39  1274.7  836.25
#Mann= 3 , 0 , 0
       0      .1       0   554.7    .045       0   579.7      .1       0
Bank Sta=554.7,579.7
XS Rating Curve= 0 ,0
Exp/Cntr=0.3,0.1

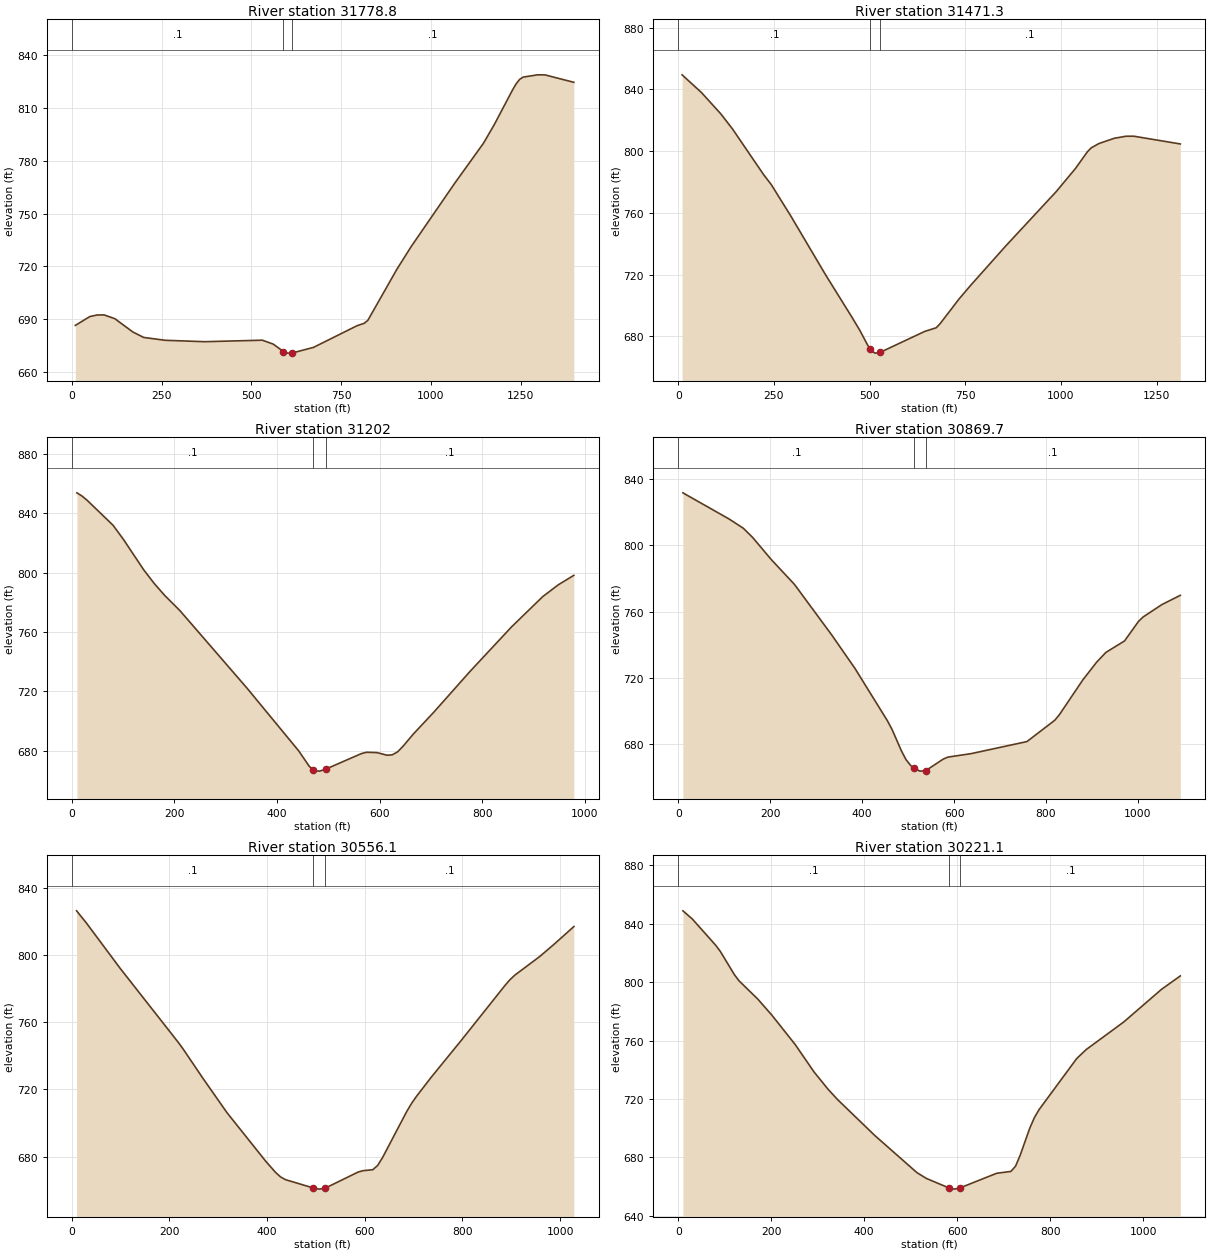
Type RM Length L Ch R = 1 ,31778.8 ,342.9,307.5,272.2
XS GIS Cut Line= 4
     1518762.186      415999.927     1518942.545      416488.217
     1518982.136      416708.167     1519422.037      417192.058
#Sta/Elev= 30
      10  686.44    50.1  691.44    70.1  692.35    90.1   692.4   120.1  690.23
   170.2  682.69   200.2  679.61   260.3  677.98   370.4  677.18   530.7  678.04
   561.2  675.78   589.3  671.59   601.8  670.69   614.3   670.8   672.9  673.93
   794.3  686.26   814.4  687.64   824.5  689.34     905  718.25   945.2  731.27
    1066  767.12  1146.5  789.98  1176.6  800.58  1226.9  820.05    1237  823.59
  1247.1  826.24  1257.1  827.52  1297.4  828.81  1317.5  828.78    1398  824.56
#Mann= 3 , 0 , 0
       0      .1       0   589.3    .045       0   614.3      .1       0
Bank Sta=589.3,614.3
XS Rating Curve= 0 ,0
Exp/Cntr=0.3,0.1

Type RM Length L Ch R = 1 ,31471.3 ,272.7,269.3,265.8
XS GIS Cut Line= 4
     1518320.941      416877.035     1518696.201      416791.748
     1519012.929      416831.339     1519419.688      417283.325
#Sta/Elev= 30
    10.1  849.45    60.8  837.96   111.4  824.13   141.8   814.4   222.8  784.92
   243.1  778.35   293.7  758.22   384.8  720.02   454.7  692.16   474.6  683.93
   494.6  674.57     502  671.71   504.5  670.74   514.5  669.18     527   669.6
   644.2  683.24   674.1   685.6   684.1  688.18   734.4  704.42   764.8  713.25
     856  738.61   987.8   773.8  1038.5   788.9  1068.9  799.48    1079  802.11
  1099.3  804.92  1139.8  808.37  1170.2  809.67  1190.5  809.69  1312.1  804.67
#Mann= 3 , 0 , 0
       0      .1       0     502    .045       0     527      .1       0
Bank Sta=502,527
XS Rating Curve= 0 ,0
Exp/Cntr=0.3,0.1

Type RM Length L Ch R = 1 ,31202   ,329,332.3,336
XS GIS Cut Line= 4
     1518347.014      417063.131     1518728.588      417077.622
      1518931.45      417077.622     1519303.364      417208.033
#Sta/Elev= 30
      10  853.92    20.1  851.73    30.1  848.84    80.4  832.07   100.5   822.6
   140.7  801.75   160.8  792.72   180.9  784.77     211  774.37   341.7  722.09
   442.7  679.65     463  669.34   470.8  667.05   473.1  666.37   483.3   666.1
   495.8  667.54   564.4   677.9   574.6  678.83   594.8  678.61     615   676.8
   625.1  677.14   635.2  679.12   645.3  682.68   665.6  691.01     706  705.96
   776.7  733.51   857.6  763.53   918.2  783.89   948.5  791.84   978.8  798.25
#Mann= 3 , 0 , 0
       0      .1       0   470.8    .045       0   495.8      .1       0
Bank Sta=470.8,495.8
XS Rating Curve= 0 ,0
Exp/Cntr=0.3,0.1

Type RM Length L Ch R = 1 ,30869.7 ,310.6,313.6,316.1
XS GIS Cut Line= 3
     1518312.088      417345.274     1518854.747       417407.01
       1519396.1      417477.881
#Sta/Elev= 30
    10.1  831.55   111.3  815.66   141.6  810.19   161.8  804.66   202.3  791.35
   252.9  776.32   333.8  745.89   384.3  725.74   455.1  694.09   465.2  688.85
   485.5  675.95   495.6  670.65   505.7  667.12   513.4  665.46   525.9  663.77
   538.4  664.08   576.5  671.03   586.6  672.22   637.2  674.32   758.5  681.59
   819.1  694.45   829.3  697.88   879.8  718.66   910.1  729.46   930.4  735.38
   970.8  742.25  1001.1  754.01  1011.2   756.7  1051.7  764.13  1092.1  769.76
#Mann= 3 , 0 , 0
       0      .1       0   513.4    .045       0   538.4      .1       0
Bank Sta=513.4,538.4
XS Rating Curve= 0 ,0
Exp/Cntr=0.3,0.1

Type RM Length L Ch R = 1 ,30556.1 ,337.8,335,331.4
XS GIS Cut Line= 4
     1518287.093      417605.564      1518608.22       417671.55
     1518938.146      417746.333     1519298.865      417777.126
#Sta/Elev= 30
     9.9  826.16    29.8  818.98    99.3  791.87   218.6  747.74   228.5  743.78
   268.2   726.7   317.9  706.08   397.5   677.1   417.4  670.54   427.3  667.92
   437.3  666.27   494.4  661.31   506.9   660.6   519.4  661.22   586.5  670.77
   596.5  671.57   616.4  672.14   626.3  674.64   636.3  679.29   686.2  706.89
   696.3  711.79   706.4  715.97   736.5  727.29   796.9  748.82   887.4  781.84
   897.4   785.2   907.5  787.92   957.8  798.86   987.9  806.31  1028.2  816.79
#Mann= 3 , 0 , 0
       0      .1       0   494.4    .045       0   519.4      .1       0
Bank Sta=494.4,519.4
XS Rating Curve= 0 ,0
Exp/Cntr=0.3,0.1

Type RM Length L Ch R = 1 ,30221.1 ,483.8,508.3,533.7
XS GIS Cut Line= 3
     1518155.123      417961.884     1518744.568      418034.961
      1519228.48      418080.657
#Sta/Elev= 30
    10.1  848.92    30.2  843.35    80.5  825.38    90.6  821.08   120.8   805.2
   130.9  800.94   171.1  788.47   201.3  777.49   251.7  757.27   291.9  738.64
   322.1  726.76   342.3  719.74   422.8     695   513.4  669.58   533.6   665.6
   581.5  659.18     594  658.25   606.5  659.15   685.1  669.11   715.5  670.38
   725.6  673.97   735.7  681.61     756  699.84   766.1  707.23   776.2  712.73
   857.2  747.73   877.5  753.85   958.5  772.81  1039.5  795.11    1080  804.33
#Mann= 3 , 0 , 0
       0      .1       0   581.5    .045       0   606.5      .1       0
Bank Sta=581.5,606.5
XS Rating Curve= 0 ,0
Exp/Cntr=0.3,0.1