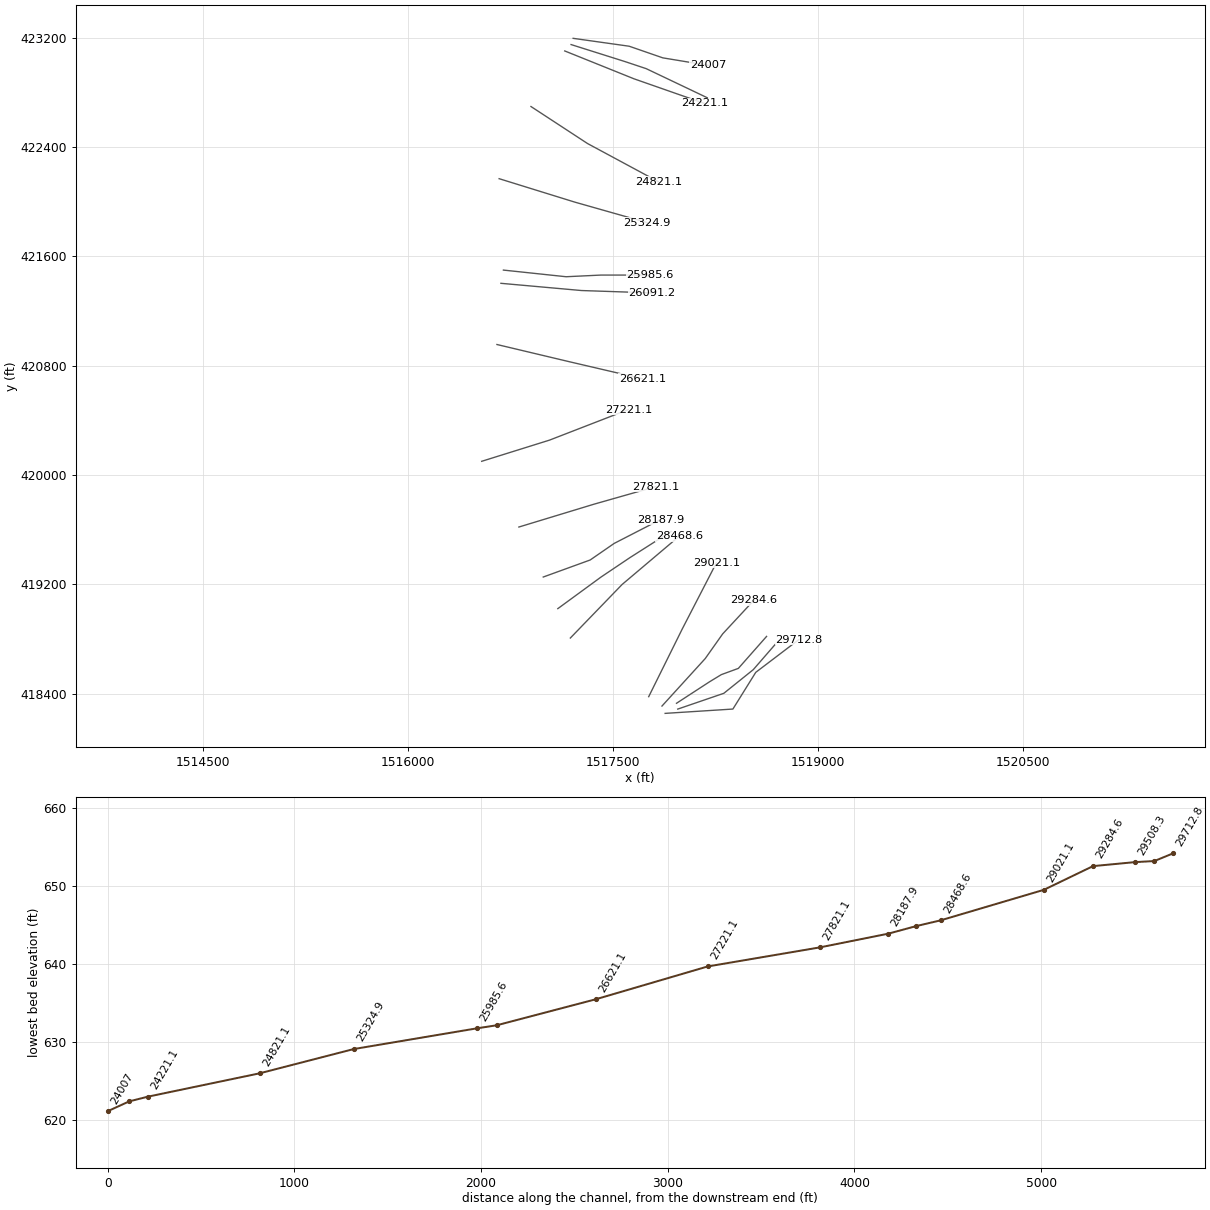
HEC-RAS study HURICANCR.prj: HURICANCR

--- HURICANCR.g01 (geometry) --- (continued)

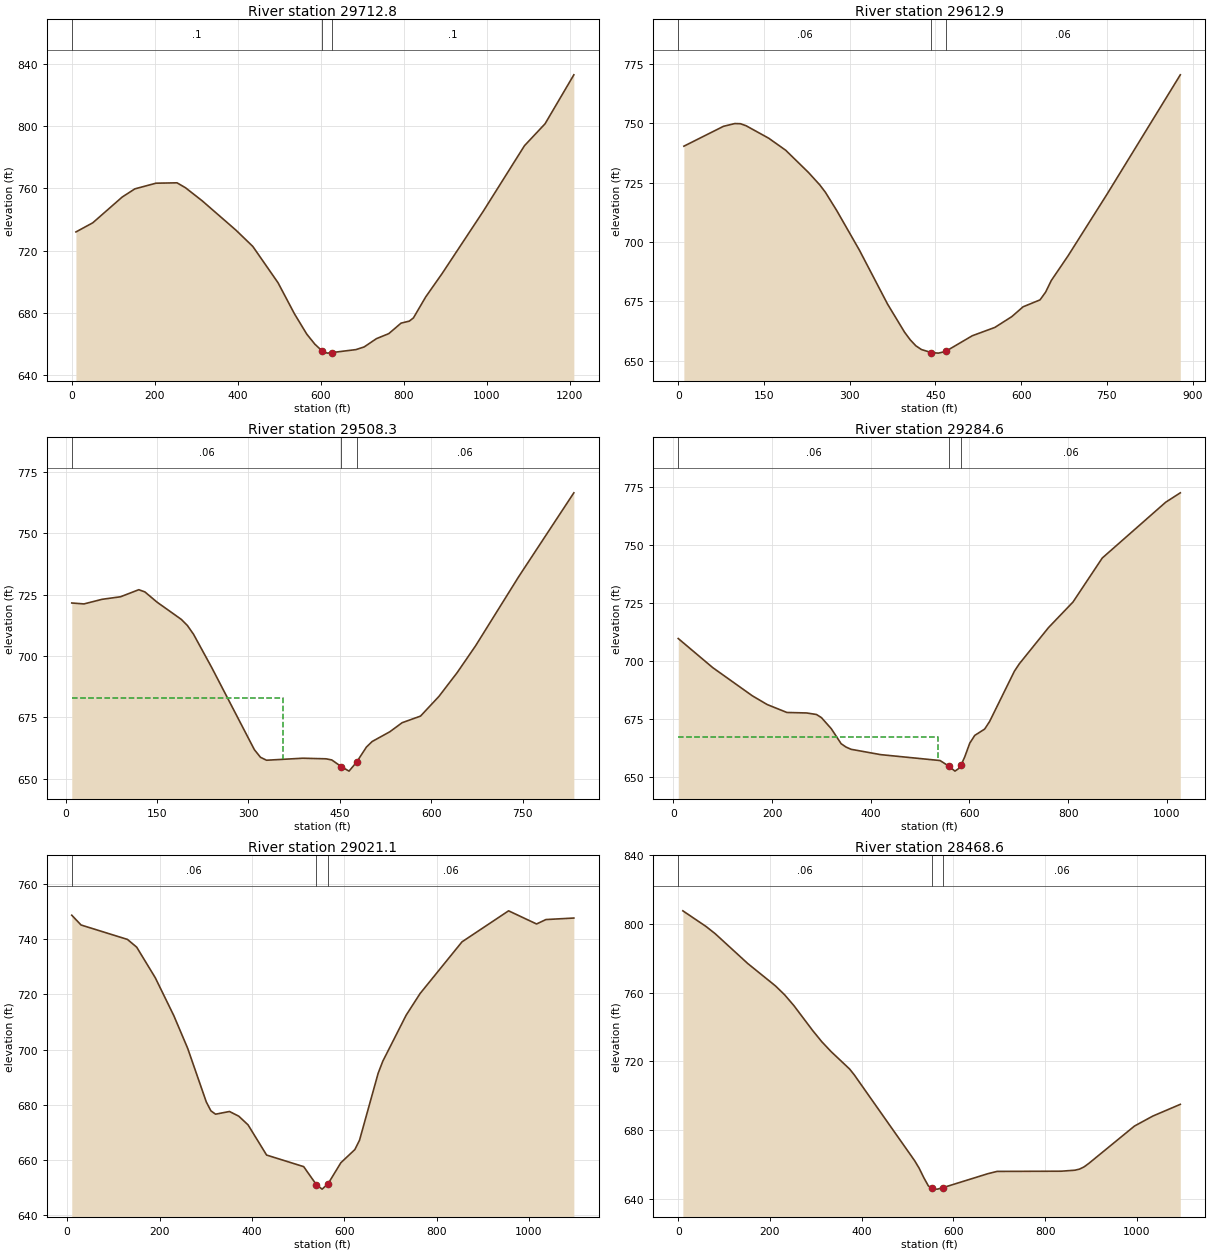
Type RM Length L Ch R = 1 ,29712.8 ,108,99.8,91.7
XS GIS Cut Line= 4
     1517883.463       418255.75     1518379.472       418287.41
     1518546.634       418555.75     1518862.476      418795.576
#Sta/Elev= 30
    10.1  732.01    50.7  737.89   121.7  754.46   152.1  759.67   202.9  763.31
   253.6  763.55   273.9  760.41   314.4  751.96   395.6  733.14   436.2   722.7
     497  699.37   536.5  679.44   566.2  666.38   585.9  659.86   603.1   655.6
   615.6  654.17   628.1  654.57   684.7  656.43   704.5  658.15   734.1  663.47
   763.8  666.69   793.4  673.43   813.2  674.73   823.1  676.75   852.8  690.28
   892.5  705.36   991.6  745.35  1090.8   787.4  1140.3  801.46  1209.7  832.91
#Mann= 3 , 0 , 0
       0      .1       0   603.1    .045       0   628.1      .1       0
Bank Sta=603.1,628.1
XS Rating Curve= 0 ,0
Exp/Cntr=0.3,0.1

Type RM Length L Ch R = 1 ,29612.9 ,114.9,104.6,94.3
XS GIS Cut Line= 4
      1517975.79      418287.106     1518313.048      418402.563
     1518528.772       418575.75     1518689.806       418761.09
#Sta/Elev= 30
     9.9  740.42    79.2   748.8      99  749.96   108.9  749.89   118.8  749.03
   158.4  743.77   188.1   738.7   227.7  729.39   247.6  724.13   257.5     721
   277.3  713.32   316.9  696.66   366.4  673.82     396  662.04   405.9  658.82
   415.8  656.28   425.6   654.7   442.8  653.43   455.3  653.19   467.8   653.9
   514.6  660.52   554.1  664.03   583.7  668.57   603.5  672.72   633.1  675.63
   642.9   678.9   652.8  683.79   682.2  694.21     751  720.43   878.6   770.5
#Mann= 3 , 0 , 0
       0     .06       0   442.8    .045       0   467.8     .06       0
Bank Sta=442.8,467.8
XS Rating Curve= 0 ,0
Exp/Cntr=0.3,0.1

Type RM Length L Ch R = 1 ,29508.3 ,207,223.7,240.4
XS GIS Cut Line= 5
     1517966.675      418329.643     1518209.744      418487.638
     1518294.818       418539.29     1518419.391      418584.865
        1518626.      418818.819
#Sta/Elev= 30
      10  721.58      30   721.2      60  723.09      90  724.11     120  726.99
     130   726.1     150  721.92   189.9  714.88   199.9  712.38   209.9  708.83
   239.9   695.2   309.8  661.78   319.8  658.69   329.7  657.49   389.4  658.31
   427.3  658.07   436.8  657.61   452.7  654.85  465.14  653.05   477.7  656.75
   493.7  662.86   503.1  665.12   532.1  669.09   552.3  672.78   582.5  675.48
   612.7  683.49   642.9  693.28   673.1  704.21   743.6  732.28   834.2  766.48
#Mann= 3 , 0 , 0
      10     .06       0   452.7    .045       0   477.7     .06       0
#XS Ineff= 2 , 0
          357.55  682.83
Permanent Ineff=
       F       F
Bank Sta=452.7,477.7
XS Rating Curve= 0 ,0
Exp/Cntr=0.3,0.1

Type RM Length L Ch R = 1 ,29284.6 ,259.2,263.5,267.3
XS GIS Cut Line= 4
     1517860.389      418309.405     1518177.118      418656.927
     1518304.689      418837.286     1518533.437      419083.631
#Sta/Elev= 30
      10  709.79      80  697.21   160.1  685.07   190.1   681.3   230.1  677.87
   270.1  677.65   290.1  676.99   300.1  675.65   320.1  670.86   340.1  664.37
   350.1  662.92   360.2  661.96   420.2  659.66   540.5  657.11   558.1  654.71
  570.71  652.54   580.7  654.03   583.1  655.17   590.7  658.78   600.7  664.62
   610.8  667.96   630.9   670.7   640.9  673.97   691.1  695.66     701  698.84
   760.3  714.52   809.8  725.53   869.1  744.53   997.6  768.62  1027.3  772.69
#Mann= 3 , 0 , 0
      10     .06       0   558.1    .045       0   583.1     .06       0
#XS Ineff= 2 , 0
          536.51  667.11
Permanent Ineff=
       F       F
Bank Sta=558.1,583.1
XS Rating Curve= 0 ,0
Exp/Cntr=0.3,0.1

Type RM Length L Ch R = 1 ,29021.1 ,562,552.5,541.7
XS GIS Cut Line= 3
     1517763.219       418378.01     1518008.583       418872.89
     1518258.622      419356.952
#Sta/Elev= 30
      10  748.65    30.1  745.11   130.6  739.89   150.6  737.08   190.8  726.03
     231  712.29   261.1  700.42   301.3  681.06   311.3  677.84   321.4  676.63
   351.5   677.6   371.6  675.91   391.7  672.77   431.9  661.83   512.2  657.64
   539.9  651.06   552.1   649.5   564.9  651.42   592.7  659.05     623  663.82
   633.1   667.2   673.4  691.42   683.5   695.8     734  712.44   764.2  720.29
     855  739.01   955.9  750.24  1016.5  745.48  1036.7  747.08  1097.2  747.63
#Mann= 3 , 0 , 0
      10     .06       0   539.9    .045       0   564.9     .06       0
Bank Sta=539.9,564.9
XS Rating Curve= 0 ,0
Exp/Cntr=0.3,0.1

Type RM Length L Ch R = 1 ,28468.6 ,136.3,131.5,128.5
XS GIS Cut Line= 3
     1517189.651      418807.059     1517568.883      419199.042
     1517988.569      419553.536
#Sta/Elev= 30
    10.1   807.7    60.6  798.59    80.8  794.33   151.5  777.03   212.1  763.95
   232.3   758.7   252.5  752.39   292.9  738.06   313.1  731.44   333.3  725.71
   373.7  715.55   383.8  712.17   515.1  662.31   525.2  657.85   535.3  652.36
   545.4  647.47   552.9  646.11   555.4  645.65   565.4  645.59   577.9   646.5
   675.3  654.59   695.2  655.91   835.1  656.03     865  656.61     875  657.25
     885  658.56     895  660.51   994.9  682.34  1034.8  688.14  1094.8  694.98
#Mann= 3 , 0 , 0
       0     .06       0   552.9    .045       0   577.9     .06       0
Bank Sta=552.9,577.9
XS Rating Curve= 0 ,0
Exp/Cntr=0.3,0.1

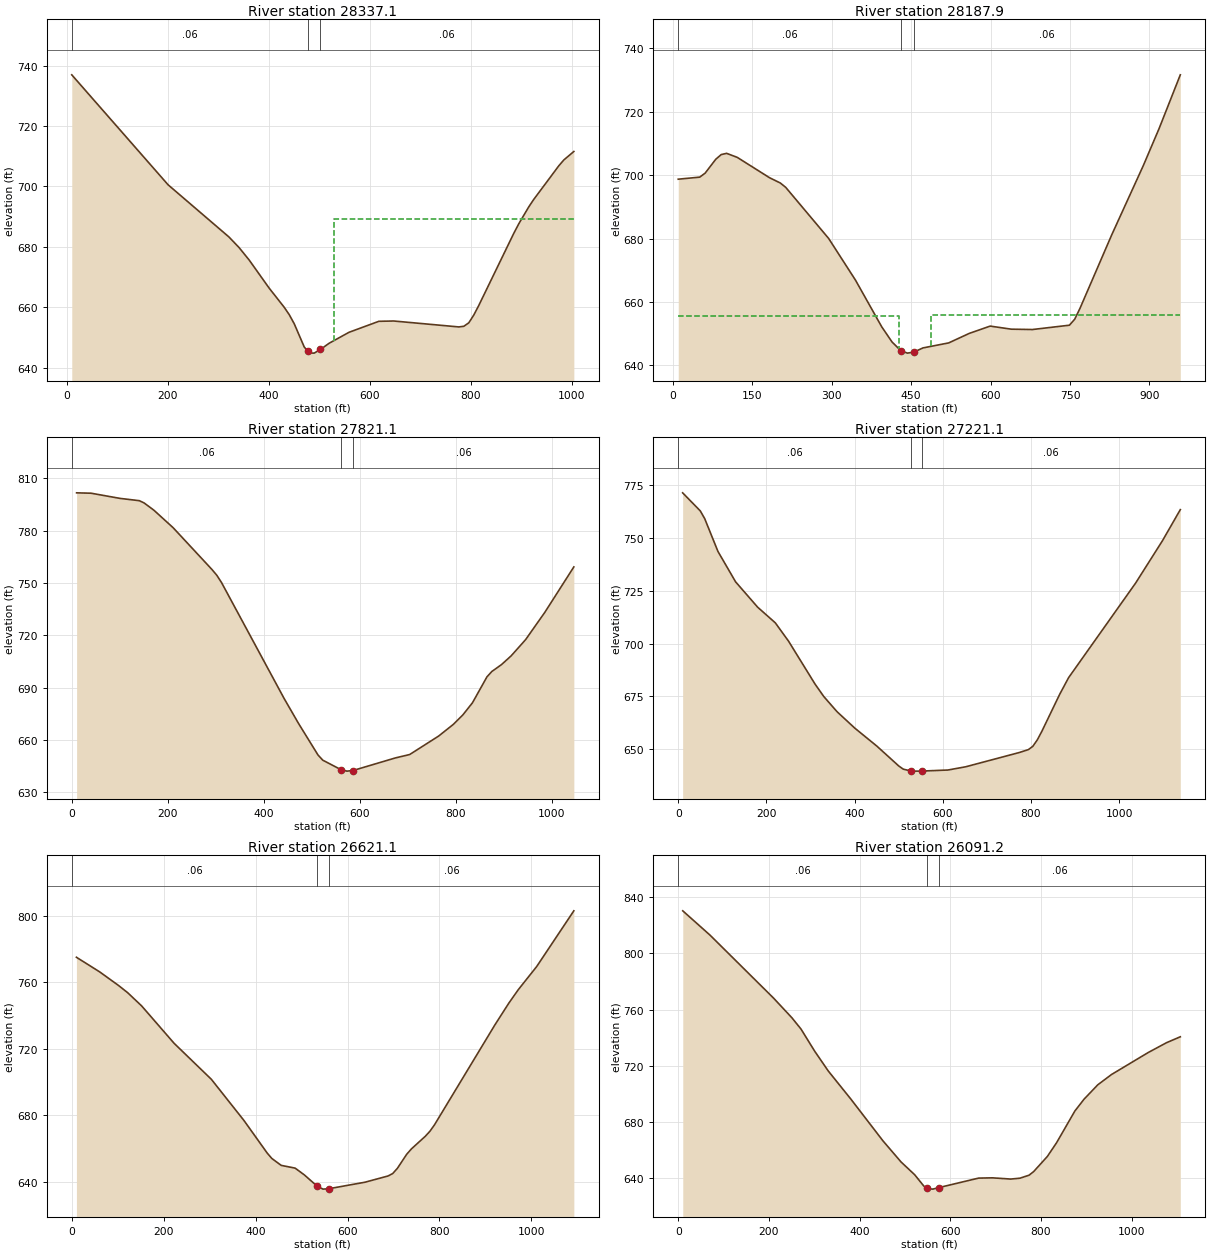
Type RM Length L Ch R = 1 ,28337.1 ,148.8,149.2,149.5
XS GIS Cut Line= 4
     1517097.907       419021.98     1517413.897      419252.896
     1517626.583      419395.699     1517927.381      419587.116
#Sta/Elev= 30
      10  736.95   200.7  700.56   321.1  683.31   341.2   679.8   361.3  675.65
   401.2  666.28   430.8  659.99   440.6  657.57   450.5  654.56   470.2  646.92
   477.4  645.44     480  644.91   489.9  644.85   502.4  646.06   519.5  648.11
   558.9  651.74     618  655.38   647.6  655.48   776.3  653.52   786.2  653.73
   796.1  654.88     806  657.46   815.9  660.63   885.2   684.5   895.1  687.66
     915  693.29   924.9  695.76   974.4  706.86   984.3  708.78  1004.1  711.58
#Mann= 3 , 0 , 0
      10     .06       0   477.4    .045       0   502.4     .06       0
#XS Ineff= 2 , 0
                          528.43          689.08
Permanent Ineff=
       F       F
Bank Sta=477.4,502.4
XS Rating Curve= 0 ,0
Exp/Cntr=0.3,0.1

Type RM Length L Ch R = 1 ,28187.9 ,375.1,366.8,358
XS GIS Cut Line= 4
      1516991.36      419253.305     1517334.695      419377.878
      1517510.92      419499.413     1517848.179        419672.6
#Sta/Elev= 30
    10.1  698.71    50.7  699.36    60.9  700.62    81.2  705.03    91.3  706.47
   101.5  706.86   121.7  705.58   182.6  699.17   202.9  697.51   213.1  696.14
   294.2  680.03   344.9  666.89   394.4  652.19   413.9   647.4   430.6  644.64
   443.1  643.88   455.6  644.23   472.3  645.52   520.9   647.1   559.8   650.1
   599.3   652.4   639.2  651.43   679.1  651.32   748.9  652.68   758.9  654.56
   768.9  657.99   828.7   681.1   888.6  703.03   918.5  714.74   958.4  731.61
#Mann= 3 , 0 , 0
    10.1     .06       0   430.6    .045       0   455.6     .06       0
#XS Ineff= 2 , 0
          427.59  655.65  486.85          656.04
Permanent Ineff=
       F       F
Bank Sta=430.6,455.6
XS Rating Curve= 0 ,0
Exp/Cntr=0.3,0.1

Type RM Length L Ch R = 1 ,27821.1 ,600.1,600,602.5
XS GIS Cut Line= 3
     1516812.839      419618.996     1517361.629      419785.735
     1517816.399      419915.043
#Sta/Elev= 30
    10.1  801.76    40.2  801.54   100.6  798.57   140.9  797.25   150.9  795.93
   171.1  791.81   211.3  781.74   291.8  757.89   301.9  754.61   311.9   750.4
   442.7  683.72   472.9  669.34   513.2  651.37   523.2  648.39   561.1  642.96
   573.6  642.12   586.1  642.47   674.2  649.67   704.3  651.65   764.7  662.25
   794.9  668.86     815  674.34   835.1  681.32   865.3  696.19   875.3  699.23
   895.5   703.2   915.6   708.2   945.8  717.52     986  733.24  1046.4  759.26
#Mann= 3 , 0 , 0
       0     .06       0   561.1    .045       0   586.1     .06       0
Bank Sta=561.1,586.1
XS Rating Curve= 0 ,0
Exp/Cntr=0.3,0.1

Type RM Length L Ch R = 1 ,27221.1 ,614.8,600,583.3
XS GIS Cut Line= 3
     1516540.688      420099.801     1517037.407      420254.852
     1517614.045      420478.116
#Sta/Elev= 30
      10  771.37      50  762.82      60  759.17    90.1  743.63   130.1  729.25
   180.1  717.26   220.2  709.84   250.2  701.18   310.2   680.9   330.2  674.96
   360.2   667.8   400.3  660.05   450.3  651.55   500.3  642.09   510.4  640.61
   528.1  639.73   540.6  639.68   553.1  639.71   611.6   640.2   652.1  641.74
   773.8   648.5   794.1  649.86   804.2  651.42   814.3  654.44   824.5  658.44
     865  675.97   885.3  683.89  1037.3  728.65  1098.2   748.7  1138.7  763.42
#Mann= 3 , 0 , 0
       0     .06       0   528.1    .045       0   553.1     .06       0
Bank Sta=528.1,553.1
XS Rating Curve= 0 ,0
Exp/Cntr=0.3,0.1

Type RM Length L Ch R = 1 ,26621.1 ,525.8,529.9,534
XS GIS Cut Line= 3
     1516652.344       420954.23     1517184.234      420827.849
     1517715.554      420703.962
#Sta/Elev= 30
    10.1  774.99    60.7   766.2   101.2  758.12   121.5  753.69   151.9  745.75
   222.7   723.2   303.7  701.55   374.6  676.78   425.2  657.17   435.3  653.91
   455.6  649.77     486   648.1   506.2  643.98   534.2  637.17   546.7  635.47
   559.2  635.71   637.6  639.61   688.1  643.38   698.2  644.84   708.3  647.94
   728.6  656.41   738.7  659.62     769  667.23   779.1  670.27   789.2  674.19
   920.5  734.27   950.8  747.36     971  755.32  1011.4  769.39  1092.3  802.93
#Mann= 3 , 0 , 0
       0     .06       0   534.2    .045       0   559.2     .06       0
Bank Sta=534.2,559.2
XS Rating Curve= 0 ,0
Exp/Cntr=0.3,0.1

Type RM Length L Ch R = 1 ,26091.2 ,102,105.6,109.2
XS GIS Cut Line= 3
     1516681.456      421401.907     1517270.923      421349.119
     1517786.452      421331.701
#Sta/Elev= 30
      10  830.36    70.2  813.03   210.6  768.09   250.8  754.17   270.8  746.17
   300.9  730.45     331  716.28   381.2  696.11   451.4  666.63   491.5  651.51
   521.6  642.39   541.7  634.36   549.2  632.71   561.7  632.14   574.2  633.17
   662.6  639.99     693  640.18   733.4  639.31   753.7  639.92   773.9  642.06
     784  644.61   814.3  655.41   834.6  665.16     875  687.78   895.3  696.22
   925.6  706.45   955.9  713.78  1036.8  729.44  1077.3  736.45  1107.6  740.65
#Mann= 3 , 0 , 0
       0     .06       0   549.2    .045       0   574.2     .06       0
Bank Sta=549.2,574.2
XS Rating Curve= 0 ,0
Exp/Cntr=0.3,0.1

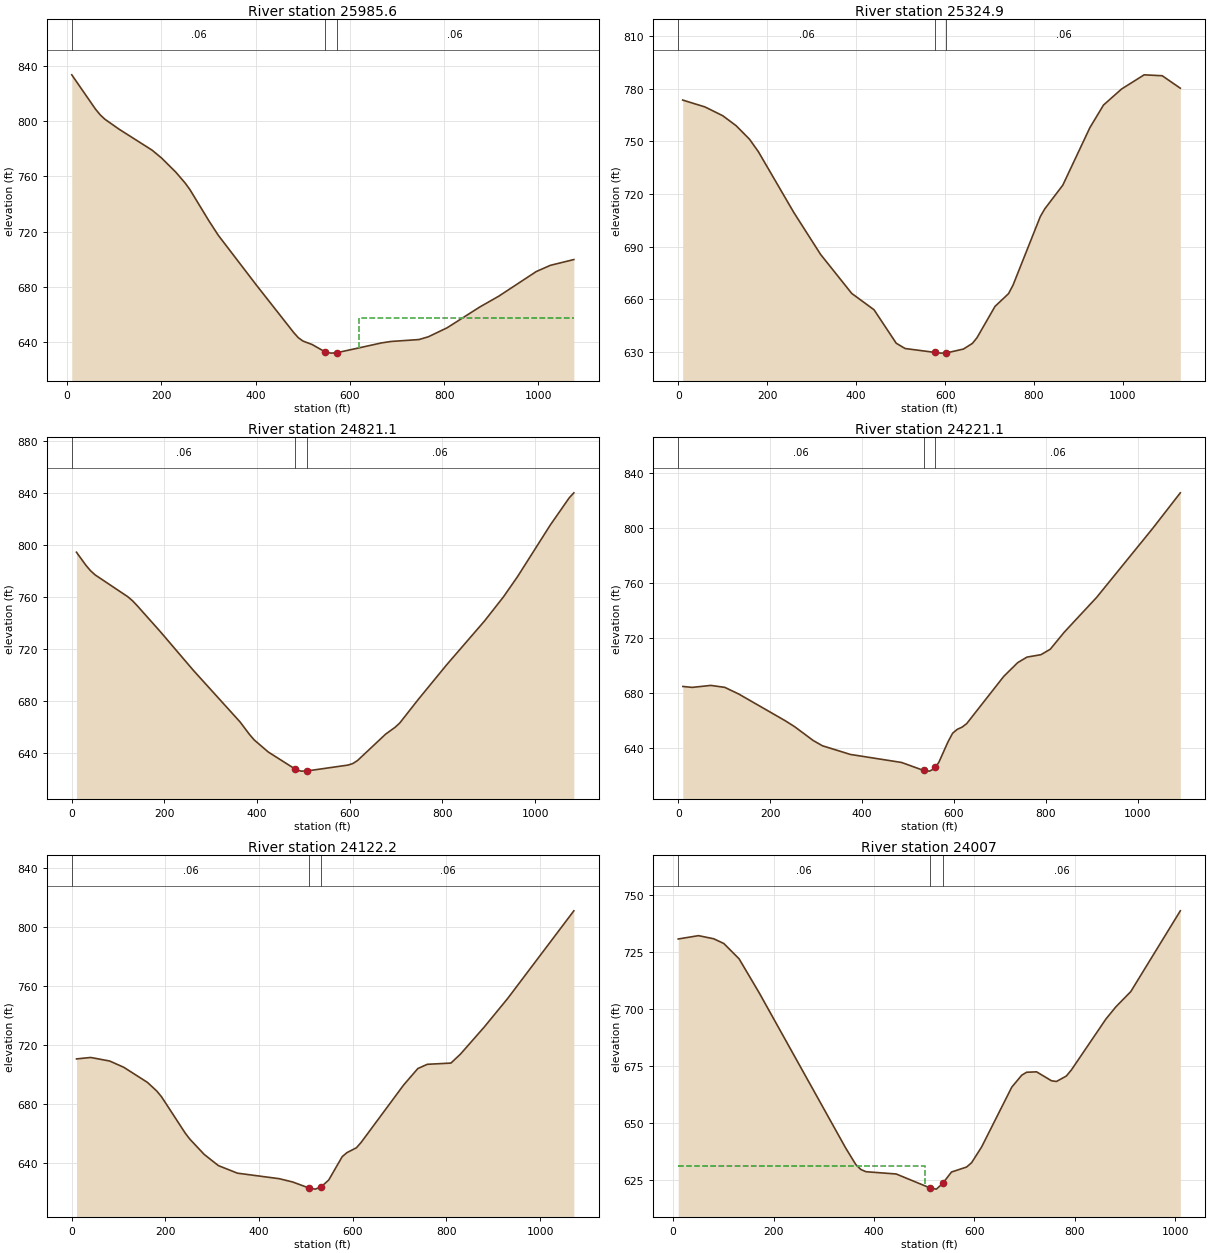
Type RM Length L Ch R = 1 ,25985.6 ,667.3,660.7,654.9
XS GIS Cut Line= 4
     1516699.677      421498.657      1517158.47      421450.043
     1517413.692      421462.197     1517772.219      421462.197
#Sta/Elev= 30
      10  833.81    60.2  808.98    70.2  804.83    80.2  801.59   110.3  794.36
   180.5   779.1   200.6  773.39   230.7  763.18   250.7   755.2   260.8  750.44
   300.9  727.86   320.9  717.32   401.2  681.41     481  646.67   490.8  642.93
   500.7   640.5   520.3  637.96   547.1  632.75   559.6  631.75   572.1  632.01
   667.7  639.19   687.4  640.21   746.8  641.61   766.7  643.63   806.5  650.14
   876.2  665.33   916.1   673.1   995.7  690.99  1025.6  695.49  1075.4  699.69
#Mann= 3 , 0 , 0
      10     .06       0   547.1    .045       0   572.1     .06       0
#XS Ineff= 2 , 0
                          619.72          657.11
Permanent Ineff=
       F       F
Bank Sta=547.1,572.1
XS Rating Curve= 0 ,0
Exp/Cntr=0.3,0.1

Type RM Length L Ch R = 1 ,25324.9 ,514.5,503.8,494.8
XS GIS Cut Line= 3
     1516668.259      422167.334     1517222.534      421995.773
     1517750.414      421846.207
#Sta/Elev= 30
      10  773.67      60  769.75     100  764.73     130  759.05   160.1  751.34
   180.1  744.22   260.1  709.35   320.1  685.48   390.1   663.2   440.2  653.88
   490.2  634.73   510.2  631.72   577.9  629.47   590.4  629.09   602.9   629.2
   641.2  631.41   661.5  634.67   671.7  637.88   712.3   655.8   742.8   663.1
   752.9  668.02   813.9  706.99   824.1  711.49   864.7  725.05   925.7  757.96
   956.2  770.82   996.8  779.97  1047.6  788.08  1088.2  787.56  1128.9  780.44
#Mann= 3 , 0 , 0
       0     .06       0   577.9    .045       0   602.9     .06       0
Bank Sta=577.9,602.9
XS Rating Curve= 0 ,0
Exp/Cntr=0.3,0.1

Type RM Length L Ch R = 1 ,24821.1 ,594.7,600,603.9
XS GIS Cut Line= 3
     1516901.406      422695.215     1517315.376      422424.488
     1517833.995      422145.339
#Sta/Elev= 30
    10.1  794.37    30.3  784.41    40.4  780.16    50.5   776.9   121.1  760.08
   131.2  757.01   141.3  753.21   191.8  732.99   262.5  703.47   363.4  663.75
   383.6  654.18   393.7  649.99     424  640.72   482.1  627.58   494.6  625.98
   507.1  626.08   596.2  630.64   606.3  631.75   616.5  634.07   677.4  654.43
   697.7  659.67   707.9  663.01   748.5  681.42   809.4  707.89   890.7  741.42
   931.3  759.83   961.8  775.43  1032.8  815.29  1073.5  836.13  1083.6  840.04
#Mann= 3 , 0 , 0
       0     .06       0   482.1    .045       0   507.1     .06       0
Bank Sta=482.1,507.1
XS Rating Curve= 0 ,0
Exp/Cntr=0.3,0.1

Type RM Length L Ch R = 1 ,24221.1 ,97.2,98.9,99.3
XS GIS Cut Line= 3
     1517148.547      423101.792     1517655.793       422897.88
     1518171.082      422717.715
#Sta/Elev= 30
    10.1  684.63    30.4  683.96    70.9   685.4   101.2  683.99   131.6  679.15
   232.9  659.67   253.1  655.39   293.6  645.31   313.8  641.44   374.6  635.14
     486  629.29   534.2  623.45   546.7  622.98   556.8  624.68   559.2  625.75
   566.9  629.22   587.1  644.35   597.2  650.63   607.4  653.45   617.5  654.97
   627.6  657.52   708.4  691.99   738.8  702.01     759  706.02   789.3  707.77
   809.5  711.72   839.9  724.11   910.6  749.54  1031.9  799.49  1092.6  825.64
#Mann= 3 , 0 , 0
       0     .06       0   534.2    .045       0   559.2     .06       0
Bank Sta=534.2,559.2
XS Rating Curve= 0 ,0
Exp/Cntr=0.3,0.1

Type RM Length L Ch R = 1 ,24122.2 ,115.6,115.3,114.9
XS GIS Cut Line= 4
      1517194.93      423148.489     1517589.918      423023.916
     1517744.874      422972.264     1518191.514      422759.578
#Sta/Elev= 30
    10.1  710.71    40.4  711.69    80.8   709.3   111.1  705.03   161.6  694.79
   181.8  688.84   191.9  684.93   242.4  660.33   252.5  656.16   282.8  645.94
   313.1  638.34   353.6  633.22     443  629.46   471.8  627.22   507.4  623.04
   519.9  622.38   532.4  623.86   548.7  628.55   577.5   644.4   587.6  647.14
   607.8  650.42   617.9  654.05   708.7  693.02     739  704.17   759.2  707.05
   809.7  707.89   829.9  713.92   880.4  732.17   930.9  751.72  1072.2  811.17
#Mann= 3 , 0 , 0
       0     .06       0   507.4    .045       0   532.4     .06       0
Bank Sta=507.4,532.4
XS Rating Curve= 0 ,0
Exp/Cntr=0.3,0.1

Type RM Length L Ch R = 1 ,24007   ,393.5,385.9,378.2
XS GIS Cut Line= 4
     1517210.122      423194.064     1517620.301      423136.336
     1517866.409      423051.261     1518197.591      422996.571
#Sta/Elev= 30
    10.1  730.87    50.5  732.33    80.8  730.96     101  728.87   131.3  722.18
   171.8  707.09   343.5  639.23   363.7  631.95   373.8  629.76   383.9  628.77
   444.3  627.76   511.9  621.63   524.4  621.12   536.9  623.61   554.4  628.62
   584.5  630.81   594.5  632.71   614.5  639.63   674.6  665.88   694.4  671.11
   704.2   672.4     724  672.58   753.6  668.67   763.5  668.35   783.2  670.73
   793.1  673.35   862.2  695.78   881.9  701.09   911.6  707.78  1010.3  743.22
#Mann= 3 , 0 , 0
    10.1     .06       0   511.9    .045       0   536.9     .06       0
#XS Ineff= 2 , 0
          501.96  631.22
Permanent Ineff=
       F       F
Bank Sta=511.9,536.9
XS Rating Curve= 0 ,0
Exp/Cntr=0.3,0.1