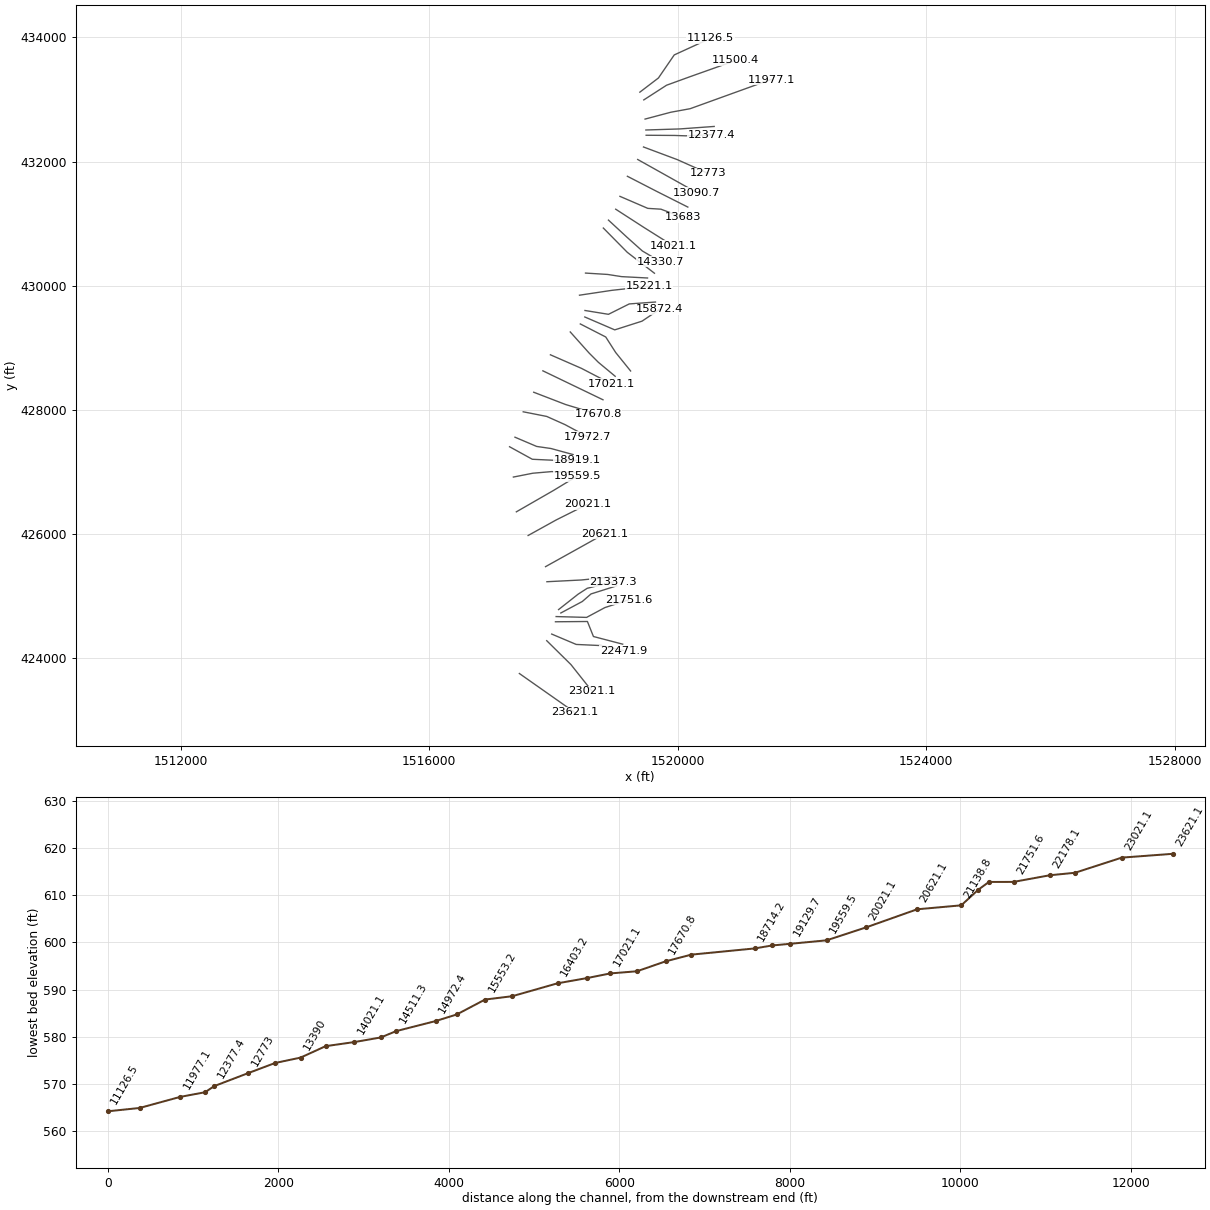
HEC-RAS study HURICANCR.prj: HURICANCR

--- HURICANCR.g01 (geometry) --- (continued)

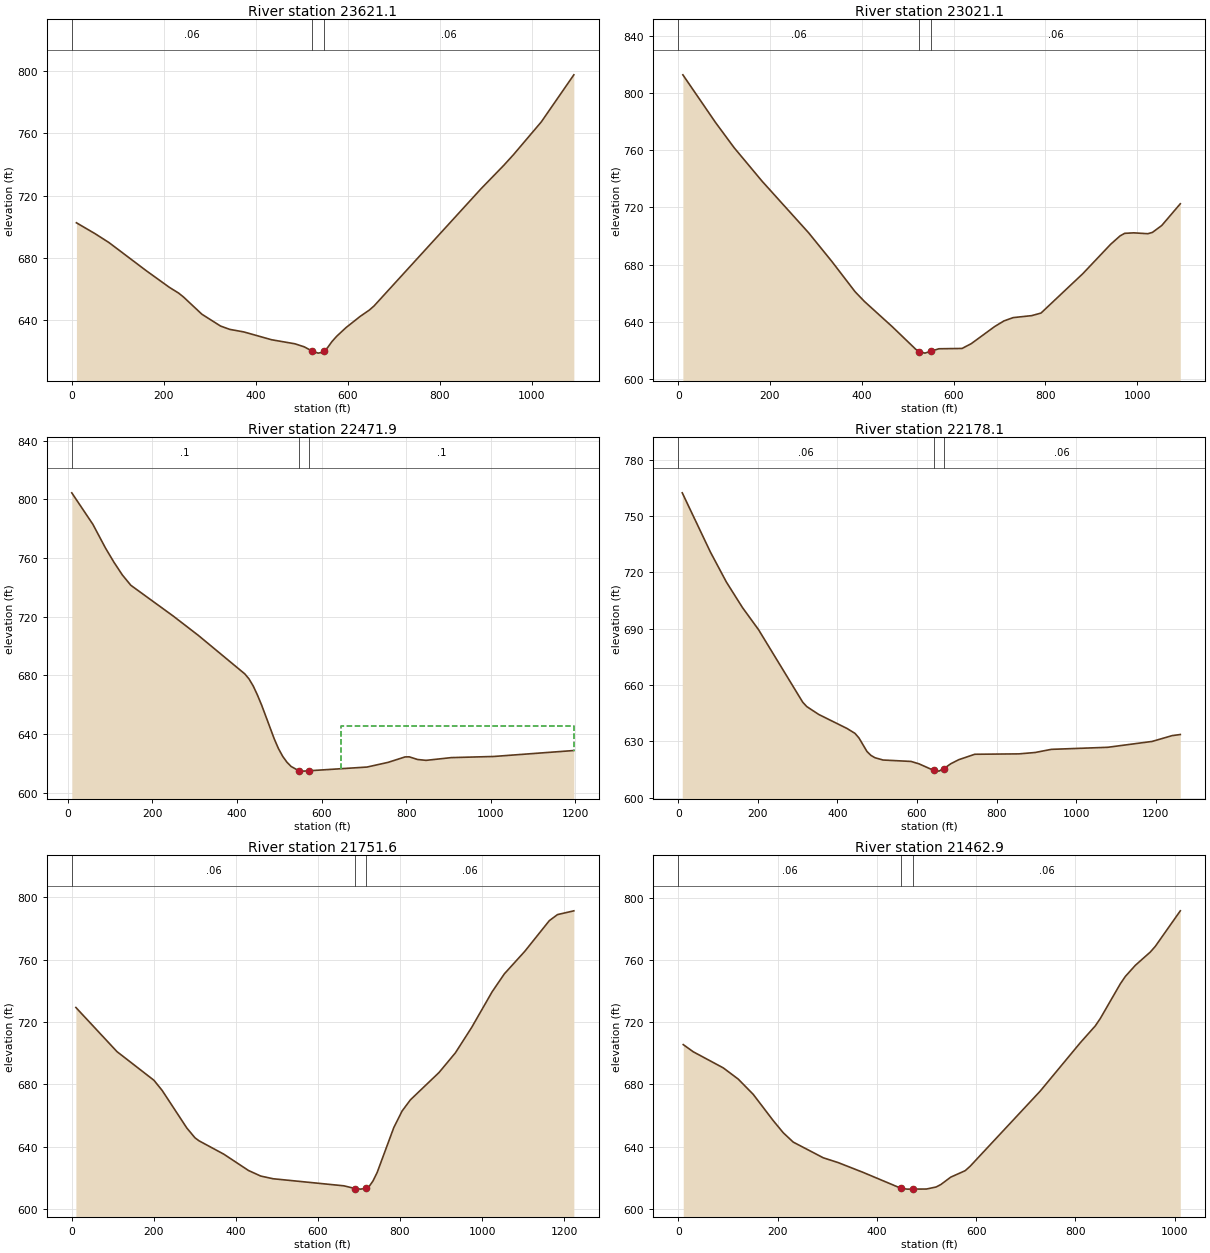
Type RM Length L Ch R = 1 ,23621.1 ,604.6,600,592.1
XS GIS Cut Line= 3
     1517450.986      423753.255      1517897.72      423439.338
     1518344.455      423125.421
#Sta/Elev= 30
    10.1  702.52    50.6  695.53    80.9  689.81   161.8  671.77   212.3  661.04
   232.6   657.3   242.7  654.91   283.1  643.75   323.6  636.17   343.8  634.02
   374.1   632.4   434.8  627.35   485.3  624.77   505.6  622.81   523.4     620
   535.9  618.77     546  619.33   548.4  620.01   556.1   622.2   566.2  626.31
   576.3  629.63   596.6   635.2   626.9  642.29   647.1  646.42   657.2     649
   889.8  724.27   940.3  739.64   960.6  746.24  1021.2  767.33    1092  797.58
#Mann= 3 , 0 , 0
       0     .06       0   523.4    .045       0   548.4     .06       0
Bank Sta=523.4,548.4
XS Rating Curve= 0 ,0
Exp/Cntr=0.3,0.1

Type RM Length L Ch R = 1 ,23021.1 ,529.1,549.2,572.3
XS GIS Cut Line= 3
     1517891.494      424281.838     1518281.401      423897.008
      1518620.95      423468.779
#Sta/Elev= 30
    10.1  812.92    81.2  779.57   121.7  761.92   182.6  738.46   284.1  702.29
   334.8   682.2   385.5  660.96   405.8  654.17   466.7  636.42   517.4  620.74
   525.2     619   537.7  617.96   550.2  619.26   568.1  621.01   618.7  621.24
   638.9  624.64   689.5  636.55   709.8   640.5     730  642.84   770.5  644.23
   790.7  646.03   881.8  673.62   942.5  694.22   962.8  700.03   972.9  701.87
   993.1  702.22  1023.5  701.62  1033.6  702.55  1053.9  707.38  1094.3  722.59
#Mann= 3 , 0 , 0
       0     .06       0   525.2    .045       0   550.2     .06       0
Bank Sta=525.2,550.2
XS Rating Curve= 0 ,0
Exp/Cntr=0.3,0.1

Type RM Length L Ch R = 1 ,22471.9 ,325.4,293.8,262.6
XS GIS Cut Line= 4
     1517971.408      424388.658     1518366.275       424221.67
     1518774.095      424202.774     1519124.403      424123.612
#Sta/Elev= 30
      10  804.55    59.8  783.11    89.7  766.87   109.7  757.19   129.6   748.5
   149.6  741.48   249.3  720.59   309.1   707.3   418.8  681.06   428.7  677.65
   438.7   672.8   448.6  666.68   458.6  659.73   488.5  636.64   498.4  630.07
   508.4   624.8   518.3  620.84   528.3  617.91   545.7  615.12   558.2  614.75
   570.7     615   707.5  617.53   757.3  620.73   797.2  624.42   807.1   624.5
     827  622.68     847   622.1   906.8  623.97  1006.6  624.74  1196.1   628.8
#Mann= 3 , 0 , 0
      10      .1       0   545.7    .045       0   570.7      .1       0
#XS Ineff= 2 , 0
                          646.18          645.65
Permanent Ineff=
       F       F
Bank Sta=545.7,570.7
XS Rating Curve= 0 ,0
Exp/Cntr=0.3,0.1

Type RM Length L Ch R = 1 ,22178.1 ,379.9,426.5,472.9
XS GIS Cut Line= 4
     1518031.951      424586.788     1518546.634      424591.187
     1518643.413      424349.241     1519114.106      424226.069
#Sta/Elev= 30
    10.1  762.32    80.7  730.87   121.1  714.81   161.5  701.25   201.8  689.51
   312.9  650.89     323  648.58   353.2  644.38   423.9  636.96   444.1  634.34
   454.1  631.92   474.3  624.69   484.4  622.58   494.5  621.36   514.7  620.14
   584.9  619.39   604.9  618.13   642.5  614.57     655  614.23   667.5  615.53
   685.1  618.18   705.1  620.32   745.2   623.2   856.4  623.41   896.9  624.14
   937.5  625.81  1079.4  626.91  1190.9  630.03  1241.6  633.14  1261.8  633.71
#Mann= 3 , 0 , 0
       0     .06       0   642.5    .045       0   667.5     .06       0
Bank Sta=642.5,667.5
XS Rating Curve= 0 ,0
Exp/Cntr=0.3,0.1

Type RM Length L Ch R = 1 ,21751.6 ,282.7,288.7,294.9
XS GIS Cut Line= 4
     1518042.932      424670.642     1518533.437      424657.172
     1518828.171      424815.536     1519206.666      424939.207
#Sta/Elev= 30
      10   729.3   110.2  700.99   200.3  682.61   220.3   676.1   280.4  652.01
   300.4  645.69   310.4  643.76   370.5  635.24   430.6  624.78   460.6  621.19
   490.7  619.47   663.1  614.94   691.1  613.16   703.6  612.82   716.1  613.25
   723.9  614.27     734  618.03   744.2  623.49   784.7  652.25     805  662.93
   825.3  670.09     895  687.61   934.8   700.2   974.6  716.54  1024.4  739.38
  1054.2  750.87    1104  765.33  1163.7  784.96  1183.6  788.86  1223.5  791.28
#Mann= 3 , 0 , 0
       0     .06       0   691.1    .045       0   716.1     .06       0
Bank Sta=691.1,716.1
XS Rating Curve= 0 ,0
Exp/Cntr=0.3,0.1

Type RM Length L Ch R = 1 ,21462.9 ,129.5,125.6,121.7
XS GIS Cut Line= 4
     1518118.593      424728.439     1518464.967      424913.779
     1518604.731      425035.313     1519017.949      425165.963
#Sta/Elev= 30
    10.1  705.61    30.2  701.01    90.7  690.67   120.9  683.45   151.1  673.65
   191.4  656.79   211.5  649.03   231.7     643   292.1  632.94   322.3  629.83
   372.7  623.53   448.6  613.36   461.1  612.81   473.6  612.82   500.1  612.88
   519.6  614.19   529.3  615.82   548.8  620.48   578.1  624.66   588.1  627.53
   729.2  675.77   809.9  706.81   840.1  717.61   850.2  722.37   890.5  744.61
   900.6  749.35   920.7  756.48     951  765.06     961  768.69  1011.4  791.51
#Mann= 3 , 0 , 0
       0     .06       0   448.6    .045       0   473.6     .06       0
Bank Sta=448.6,473.6
XS Rating Curve= 0 ,0
Exp/Cntr=0.3,0.1

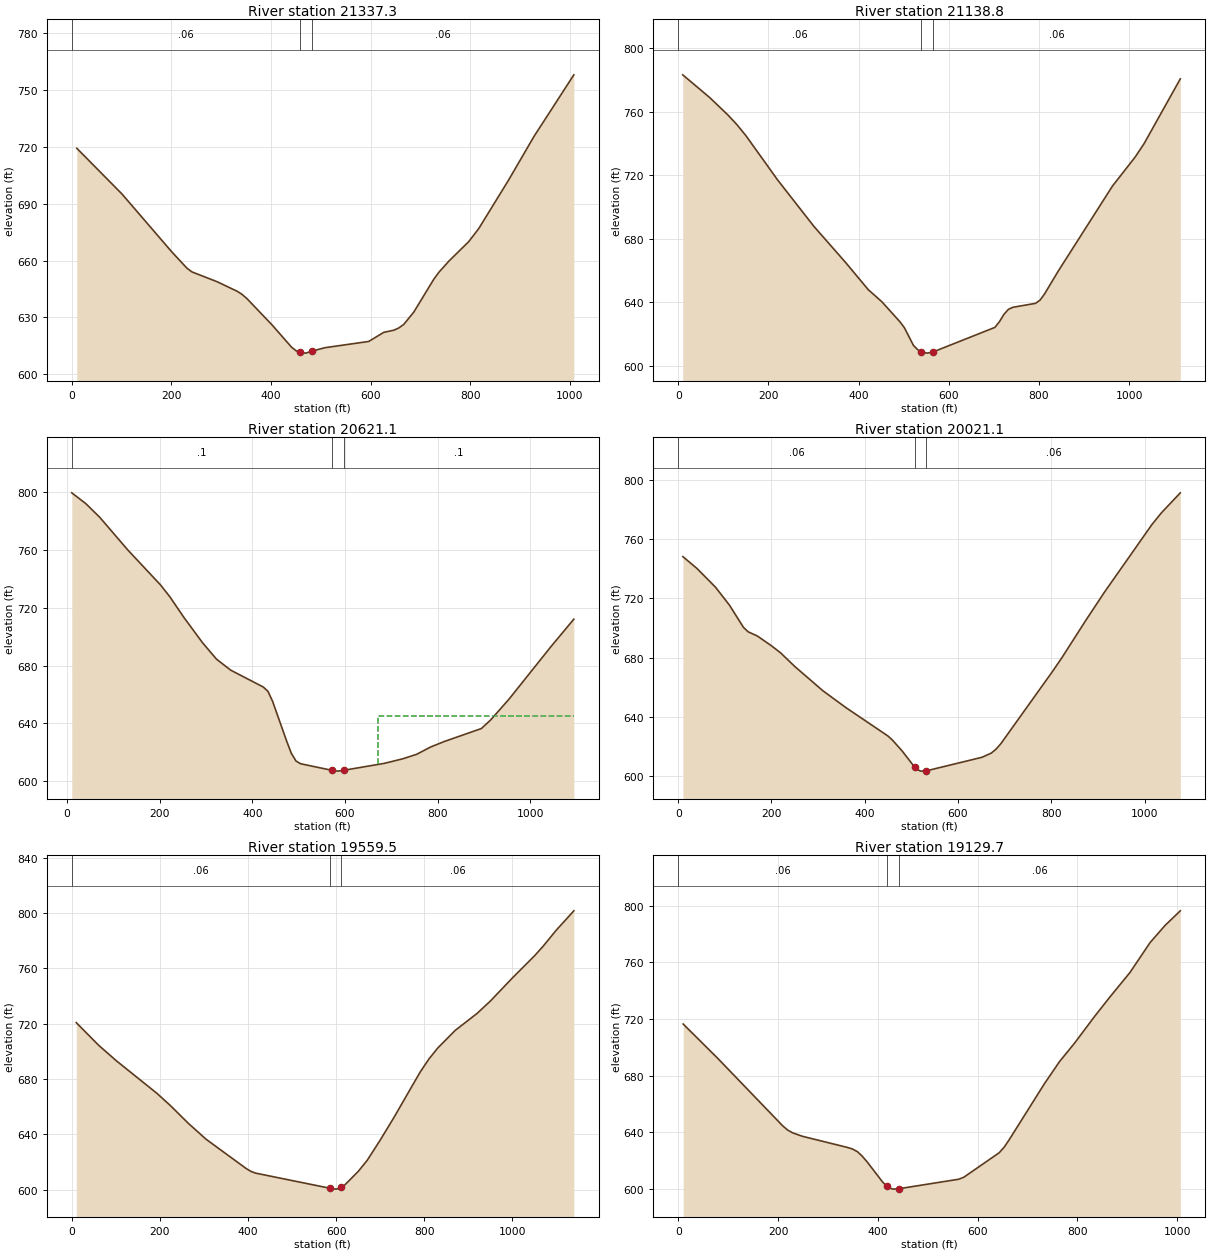
Type RM Length L Ch R = 1 ,21337.3 ,212.9,198.5,185.4
XS GIS Cut Line= 4
     1518082.133      424783.129     1518398.123      425032.275
     1518543.964      425126.464     1518963.258      425229.769
#Sta/Elev= 30
    10.1  719.23   100.6  695.16   201.2  664.45   231.4  655.91   241.4  653.98
   291.7  648.83     332  643.79     342  642.11   352.1  639.79   402.4  625.93
     441  614.34   450.6  612.34   457.4  611.56   469.9  611.15   482.4  612.23
   508.5  614.03   596.1  617.31   626.2  622.11   646.3  623.23   656.4  624.42
   666.4   626.3   686.5  632.78   726.6   650.1   736.7  653.74   756.8  659.65
   796.9     670     817  676.89   877.3  702.66   927.5  725.34  1007.8  757.98
#Mann= 3 , 0 , 0
       0     .06       0   457.4    .045       0   482.4     .06       0
Bank Sta=457.4,482.4
XS Rating Curve= 0 ,0
Exp/Cntr=0.3,0.1

Type RM Length L Ch R = 1 ,21138.8 ,505.1,517.7,529.1
XS GIS Cut Line= 3
     1517894.321      425231.884     1518445.457      425259.836
     1519004.342      425315.294
#Sta/Elev= 30
      10  783.32    70.2  768.88   110.4  757.95   130.4  751.83   150.5  744.81
   220.7  716.94     301  687.74   371.2  665.01   421.4  647.88   451.5  640.29
   491.6  627.66   501.7  623.82   521.7  612.71   531.8  609.87   539.3  608.76
   551.8  607.86   564.3  608.51   702.3  624.09   712.3  627.66   722.3  632.29
   732.4  635.51   742.4  636.77   792.5  639.25   802.6  641.33   812.6  645.24
   842.7  659.54     963  713.18  1013.2  731.42  1033.2  739.96  1113.5  780.79
#Mann= 3 , 0 , 0
       0     .06       0   539.3    .045       0   564.3     .06       0
Bank Sta=539.3,564.3
XS Rating Curve= 0 ,0
Exp/Cntr=0.3,0.1

Type RM Length L Ch R = 1 ,20621.1 ,600,600,598.8
XS GIS Cut Line= 3
     1517872.345      425474.842     1518383.652      425759.336
     1518828.171      426007.667
#Sta/Elev= 30
    10.1  799.55    40.4  792.09    70.6  782.59   131.1  760.02   201.8  735.83
   221.9  727.64   252.2  713.38   292.6   695.8   322.8  684.44   353.1  676.91
   423.7   665.2   433.8  662.21   443.9  655.21   474.2  627.74   484.2  619.37
   494.3     614   504.4  612.12   572.6  607.54   585.1  607.02   597.6  607.61
     685  612.39   724.9  615.55   754.9  618.66   784.8  623.67   814.8  627.54
   894.6  636.48   914.6  642.41   954.5  656.89  1044.4  692.97  1094.3  712.16
#Mann= 3 , 0 , 0
    10.1      .1       0   572.6    .045       0   597.6      .1       0
#XS Ineff= 2 , 0
                          671.45          645.43
Permanent Ineff=
       F       F
Bank Sta=572.6,597.6
XS Rating Curve= 0 ,0
Exp/Cntr=0.3,0.1

Type RM Length L Ch R = 1 ,20021.1 ,461.2,461.6,463.1
XS GIS Cut Line= 3
      1517592.05      425976.874     1518046.591      426228.676
     1518544.719         426478.
#Sta/Elev= 30
      10  748.31      40  740.36    79.9  727.65   109.9  715.48   139.9  700.44
   149.9  697.46   169.9  694.56   199.9  688.01   219.8  683.13   249.8  674.03
   309.8  657.67   359.7  646.13   449.7  626.96   459.7  624.07   479.7     617
   507.1  605.84   509.6  604.84   519.6  603.18   532.1  603.38   651.3  612.53
   671.5  615.41   681.7  618.08   691.8  621.73   803.2  670.87   823.5  680.29
   874.1  705.22   914.6  724.53  1015.9  770.06  1036.2  777.97  1076.7  791.49
#Mann= 3 , 0 , 0
       0     .06       0   507.1    .045       0   532.1     .06       0
Bank Sta=507.1,532.1
XS Rating Curve= 0 ,0
Exp/Cntr=0.3,0.1

Type RM Length L Ch R = 1 ,19559.5 ,441.6,429.8,418
XS GIS Cut Line= 3
     1517402.297      426357.903     1518001.158       426702.71
     1518384.719      426935.219
#Sta/Elev= 30
    10.2  720.76      61  704.42   101.6   693.1   193.1  669.73   223.6  660.93
   264.2  648.11   304.9  636.49   396.3  615.24   406.5  613.31   416.7  612.05
   587.1  601.01   599.6  600.45   609.7  601.04   612.1  601.63   619.9  603.55
   650.4   613.3   670.7  621.33     701  636.34   730.9  652.04   790.7  685.01
   810.6  694.46   830.6  702.39   870.4  715.18   920.3  727.52   950.2   736.4
    1000  753.02  1049.9   768.9  1069.8  775.95  1099.7  787.59  1139.6  801.57
#Mann= 3 , 0 , 0
       0     .06       0   587.1    .045       0   612.1     .06       0
Bank Sta=587.1,612.1
XS Rating Curve= 0 ,0
Exp/Cntr=0.3,0.1

Type RM Length L Ch R = 1 ,19129.7 ,214.5,210.6,206.8
XS GIS Cut Line= 4
     1517354.504      426918.261     1517666.833      426979.847
     1517970.365      427006.241     1518353.078      426988.645
#Sta/Elev= 30
     9.9  716.41    79.6  691.99   208.9   644.6   218.9  641.56   228.8  639.57
   248.7  637.07   338.7  629.21   348.8  628.13     359  626.21   369.1  622.86
   379.3  618.63   409.7  604.66   417.6  601.89   419.9  601.08   430.1  599.71
   442.6  600.02   562.1  606.71   572.2  608.11   643.2  625.42   653.3  629.45
   663.3  634.66   733.9  674.27   764.2  689.91   794.4  702.98   834.7  721.95
     865   735.5   905.3  752.87   945.6     774   975.9  786.22  1006.1  796.41
#Mann= 3 , 0 , 0
       0     .06       0   417.6    .045       0   442.6     .06       0
Bank Sta=417.6,442.6
XS Rating Curve= 0 ,0
Exp/Cntr=0.3,0.1

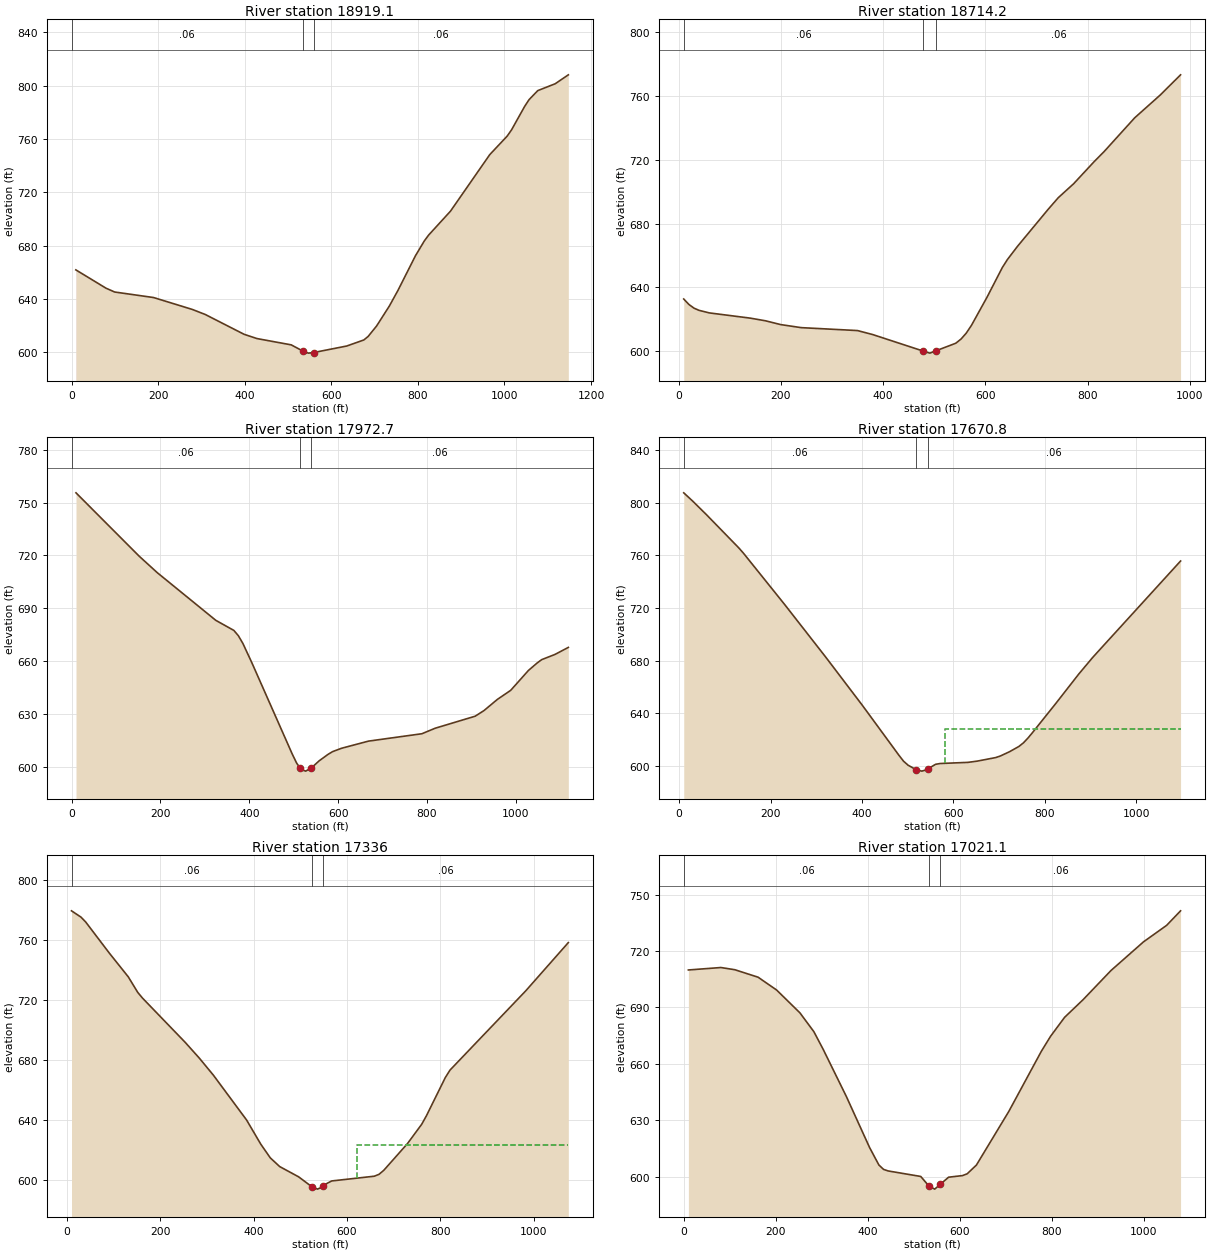
Type RM Length L Ch R = 1 ,18919.1 ,207.6,204.9,202.1
XS GIS Cut Line= 4
     1517292.918      427406.551       1517659.8      427204.706
     1517984.905      427189.514      1518388.27        427186.6
#Sta/Elev= 30
      10  661.81    79.8  648.05    99.7   645.2   189.4  641.07   279.2  632.12
   309.1  628.32   398.8  613.46   428.6  610.27   507.5  605.56   534.5  600.89
     547  599.36   559.5  599.81   635.7  604.69   675.2  609.23     685  611.81
   704.8  619.76   734.3  634.75   754.3  646.57   794.6  672.48   814.8  683.44
   824.9  687.91   875.3  705.81   966.1  748.26  1006.4  762.18  1016.5  766.89
  1046.7  784.44  1056.8  789.46    1077  796.28  1117.3  801.43  1147.6  808.12
#Mann= 3 , 0 , 0
       0     .06       0   534.5    .045       0   559.5     .06       0
Bank Sta=534.5,559.5
XS Rating Curve= 0 ,0
Exp/Cntr=0.3,0.1

Type RM Length L Ch R = 1 ,18714.2 ,749.6,741.5,733.1
XS GIS Cut Line= 4
     1517380.271      427560.194     1517729.682      427411.315
     1517960.598      427377.893     1518316.087      427280.665
#Sta/Elev= 30
      10   632.7      20   629.3      30  626.96      40  625.57      60  623.97
   139.9   620.7   169.9  619.02   199.9  616.62   239.9  614.72   349.8  612.89
   379.8  610.36   478.9  599.96  491.35  598.73   503.9  600.27   542.1  604.95
   552.3  607.55   562.4  611.22   572.6   616.1     603  633.72   633.1  652.44
     643  657.44   662.9   665.8   722.7  688.96   742.6  696.29   772.5  705.01
   812.3  718.76   832.3  725.26     892   746.4   941.8  760.66   981.7  773.37
#Mann= 3 , 0 , 0
      10     .06       0   478.9    .045       0   503.9     .06       0
Bank Sta=478.9,503.9
XS Rating Curve= 0 ,0
Exp/Cntr=0.3,0.1

Type RM Length L Ch R = 1 ,17972.7 ,300.4,301.9,304.1
XS GIS Cut Line= 4
     1517512.868      427969.624     1517891.183      427894.841
     1518185.916       427762.87     1518546.634      427569.314
#Sta/Elev= 30
    10.1  755.59   152.2   719.6   192.8  710.25   324.7  683.12   365.3  677.39
   375.5  674.36   385.6     670   405.8  659.03   496.6  607.18   506.7  601.91
   514.4  599.19   516.8  598.35   526.9  597.42   539.4  599.17   557.2  603.27
   577.4  606.98   587.5  608.51   607.6  610.41   668.2  614.47   788.4  618.67
   818.4  621.81   908.3  628.64   928.2  631.85   958.2  638.18   988.1  643.31
  1028.1  654.63    1048  658.94    1058  660.79    1088  663.76  1117.9  667.74
#Mann= 3 , 0 , 0
       0     .06       0   514.4    .045       0   539.4     .06       0
Bank Sta=514.4,539.4
XS Rating Curve= 0 ,0
Exp/Cntr=0.3,0.1

Type RM Length L Ch R = 1 ,17670.8 ,337.1,334.8,331.9
XS GIS Cut Line= 3
     1517681.752      428284.708      1518195.89      428086.582
     1518718.562      427928.218
#Sta/Elev= 30
      10  807.55    30.1  801.08    60.1   790.8   130.2  765.79   140.3  761.82
   230.4  722.84   320.6  682.71   400.7  646.08   480.9  608.04   490.9  603.58
   500.9   600.5   518.5  597.09     531     596     541  597.02   543.5   597.6
   561.1  601.19   571.2  601.79   631.9  602.66   652.1   603.6   692.6  606.31
   702.7  607.49   722.9  610.76   743.2  614.72   753.3   617.5   763.4  621.23
   773.5  625.45   824.1  647.43   874.6  669.91     905  682.49  1097.1  755.71
#Mann= 3 , 0 , 0
      10     .06       0   518.5    .045       0   543.5     .06       0
#XS Ineff= 2 , 0
                          580.79          627.96
Permanent Ineff=
       F       F
Bank Sta=518.5,543.5
XS Rating Curve= 0 ,0
Exp/Cntr=0.3,0.1

Type RM Length L Ch R = 1 ,17336   ,313.7,314.8,313.8
XS GIS Cut Line= 2
     1517829.596      428629.475     1518797.378       428163.18
#Sta/Elev= 30
    10.1  779.31    30.4  775.12    40.5  771.87    91.2  751.11   131.7  735.33
     152  724.97   162.2  721.16   253.4  691.76   283.8  681.21   314.2  669.74
   385.1  639.96   415.5  623.87   435.8  614.76   456.1  608.91   496.6  602.09
   524.6  595.57   537.1   593.9   549.6  595.68   557.4  597.73   567.5  599.35
   658.7  602.51   668.9  603.78     679  606.44   729.7  624.22   760.1  637.06
   770.2  642.69   810.8  668.24   820.9  673.22     983  725.98  1074.3  758.16
#Mann= 3 , 0 , 0
    10.1     .06       0   524.6    .045       0   549.6     .06       0
#XS Ineff= 2 , 0
                          621.85          623.03
Permanent Ineff=
       F       F
Bank Sta=524.6,549.6
XS Rating Curve= 0 ,0
Exp/Cntr=0.3,0.1

Type RM Length L Ch R = 1 ,17021.1 ,281.5,271.3,263.1
XS GIS Cut Line= 3
     1517950.858      428887.769     1518450.624      428669.232
     1518924.949      428422.721
#Sta/Elev= 30
    10.1   709.9    80.8   711.2   111.1  710.03   161.6  706.06     202  699.23
   252.5  687.13   282.8  677.14     303  667.78   353.5  642.66     404  615.54
   424.2  606.27   434.3  603.94   444.4   603.1   515.2  600.17     533  595.07
   545.5  593.44     558  596.05   575.7  599.78     606  600.63   616.1  601.57
   636.2  606.23   706.8   634.8   777.4  666.71   797.6  674.73   827.9  684.73
   868.2  694.14   928.7   709.6   999.3  724.82  1049.8  733.63    1080  741.33
#Mann= 3 , 0 , 0
       0     .06       0     533    .045       0     558     .06       0
Bank Sta=533,558
XS Rating Curve= 0 ,0
Exp/Cntr=0.3,0.1

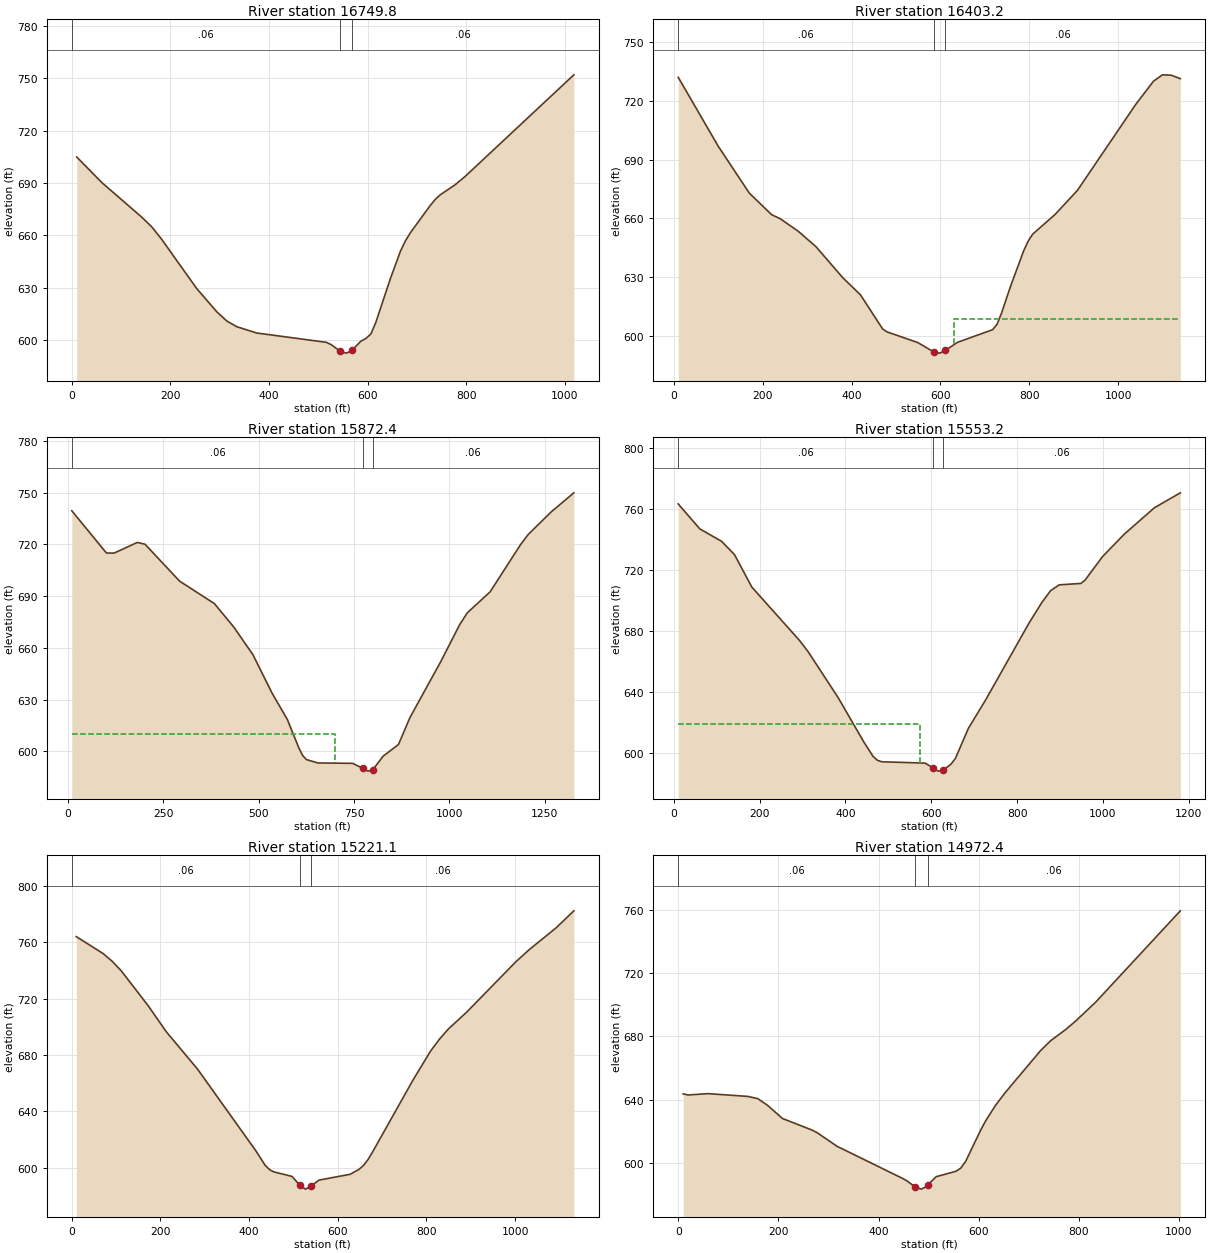
Type RM Length L Ch R = 1 ,16749.8 ,352.9,346.6,340.4
XS GIS Cut Line= 4
     1518270.511      429255.602     1518574.348      428915.305
     1518723.228      428766.425     1518993.642      428541.586
#Sta/Elev= 30
    10.1  704.88    60.8  690.27   141.9  670.41   162.2  664.86   182.5  657.65
   253.4  629.49     294   616.2   314.3  610.92   334.5  607.62   375.1     604
   516.4  598.65   526.4   597.3     544   593.6   556.5  592.46   566.5  593.55
     569  594.27   586.5  599.32   596.6  600.83   606.6  603.41   616.6  609.96
   646.7  635.52   666.7  650.89   676.8  656.84   686.8  661.45     727  677.03
   737.1   680.5   747.1  683.14   777.3  688.91   797.4  693.61  1018.4  751.98
#Mann= 3 , 0 , 0
       0     .06       0     544    .045       0     569     .06       0
Bank Sta=544,569
XS Rating Curve= 0 ,0
Exp/Cntr=0.3,0.1

Type RM Length L Ch R = 1 ,16403.2 ,494,530.8,568.2
XS GIS Cut Line= 4
     1518432.107      429384.881     1518841.368      429174.951
     1519001.501      428924.788     1519241.736      428627.187
#Sta/Elev= 30
      10  731.99     100  696.83     170  672.91     220  661.97     240   659.8
     280  653.49     320   645.6     380  629.85     420  621.06   469.9  603.65
   479.8  602.18   549.1  596.72   586.1  591.78   598.6  591.35   611.1  592.73
   638.2  596.85   717.4  603.32   727.3  606.09   737.2  611.68     757  625.04
   787.2  643.57   797.2  648.43   807.3  651.99   857.6  662.02     908  674.31
  1038.8  718.04  1079.1  729.99  1099.2  733.25  1119.3  733.05  1139.5  731.31
#Mann= 3 , 0 , 0
      10     .06       0   586.1    .045       0   611.1     .06       0
#XS Ineff= 2 , 0
                          631.25          608.68
Permanent Ineff=
       F       F
Bank Sta=586.1,611.1
XS Rating Curve= 0 ,0
Exp/Cntr=0.3,0.1

Type RM Length L Ch R = 1 ,15872.4 ,315.5,319.3,322.4
XS GIS Cut Line= 4
      1518504.18      429497.188     1518986.535      429289.326
     1519426.436      429430.094     1519707.972      429619.251
#Sta/Elev= 30
    10.1  739.47     101  714.98   121.2  714.94   181.8   721.1     202  720.09
   292.9  698.68   383.8   685.7   434.3  672.25   484.8  656.15   535.3  633.78
   575.4  618.48   605.6  601.96   615.6  597.57   625.6  595.28   655.8  593.35
   746.1  593.13   773.8  590.23   786.3  588.62   798.8   589.3   826.5  597.31
   866.6  604.06   896.7  619.68   977.1  651.93    1027  673.48    1047  680.34
  1106.8  692.48  1186.6  719.85  1206.6  725.71  1266.4  738.69  1326.3  749.85
#Mann= 3 , 0 , 0
    10.1     .06       0   773.8    .045       0   798.8     .06       0
#XS Ineff= 2 , 0
          701.14  609.89
Permanent Ineff=
       F       F
Bank Sta=773.8,798.8
XS Rating Curve= 0 ,0
Exp/Cntr=0.3,0.1

Type RM Length L Ch R = 1 ,15553.2 ,340.7,332,322.3
XS GIS Cut Line= 4
     1518507.043      429601.655     1518885.358      429540.069
     1519219.682      429707.231     1519641.987      429738.024
#Sta/Elev= 30
    10.1  763.36    60.5  746.94     111  738.85   141.2  730.11   181.6  708.79
   292.5  673.82   312.7  666.43   383.3  635.98   443.9   606.5   464.1  597.67
   474.2  595.07   484.3  594.06   585.3  593.18   603.1  590.28   615.6  587.91
   628.1  588.56     646  592.51   656.1  596.19   686.4  615.96   726.8  634.72
   827.7  685.07   857.9  698.71   878.1   706.4   898.2  710.22   948.6  711.16
   958.7  713.39     999  728.71  1049.4  743.37    1120  760.83  1180.5  770.65
#Mann= 3 , 0 , 0
    10.1     .06       0   603.1    .045       0   628.1     .06       0
#XS Ineff= 2 , 0
          573.03   618.8
Permanent Ineff=
       F       F
Bank Sta=603.1,628.1
XS Rating Curve= 0 ,0
Exp/Cntr=0.3,0.1

Type RM Length L Ch R = 1 ,15221.1 ,257,248.7,241.4
XS GIS Cut Line= 3
     1518419.063      429847.999     1518940.462      429926.351
     1519542.147      429992.814
#Sta/Elev= 30
    10.1  763.97      71  751.86    91.3   746.4   111.5  739.71   172.4   714.9
   212.9  696.56   283.9  669.85   415.7  611.75     436  601.78   446.1  598.56
   456.3  596.95   496.8  593.78   514.8   587.4   527.3  584.75   539.8  586.83
   557.5  591.13   628.1  595.29   648.3  598.83   658.4  601.69   668.5  605.82
   678.6  611.12   769.4  661.96   809.7  682.87   829.9  691.35   850.1  698.56
   890.5  710.24  1001.4  745.98  1031.7  754.63  1092.2  770.05  1132.6  782.24
#Mann= 3 , 0 , 0
       0     .06       0   514.8    .045       0   539.8     .06       0
Bank Sta=514.8,539.8
XS Rating Curve= 0 ,0
Exp/Cntr=0.3,0.1

Type RM Length L Ch R = 1 ,14972.4 ,480.8,461.2,444.3
XS GIS Cut Line= 4
     1518515.841      430204.319     1518872.161      430182.324
      1519096.51      430147.132     1519514.416      430125.137
#Sta/Elev= 30
     9.9  643.63    19.8  642.95    59.5  643.79   138.8  642.04   158.7  640.65
   178.5  636.37   208.2  628.05   267.7  620.68   277.7  619.01   317.3  610.44
   445.9  590.46   455.7   588.8   472.9   584.8   485.4  583.35   495.2  584.96
   497.9   585.9     515  591.21   554.5  594.64   564.3  596.67   574.2  601.07
     604  620.75     614  626.63   633.9  636.54   653.8  644.77   723.6  671.05
   743.5  677.24   773.4  684.29   793.3  689.65   833.2  701.58  1002.6  759.51
#Mann= 3 , 0 , 0
       0     .06       0   472.9    .045       0   497.9     .06       0
Bank Sta=472.9,497.9
XS Rating Curve= 0 ,0
Exp/Cntr=0.3,0.1

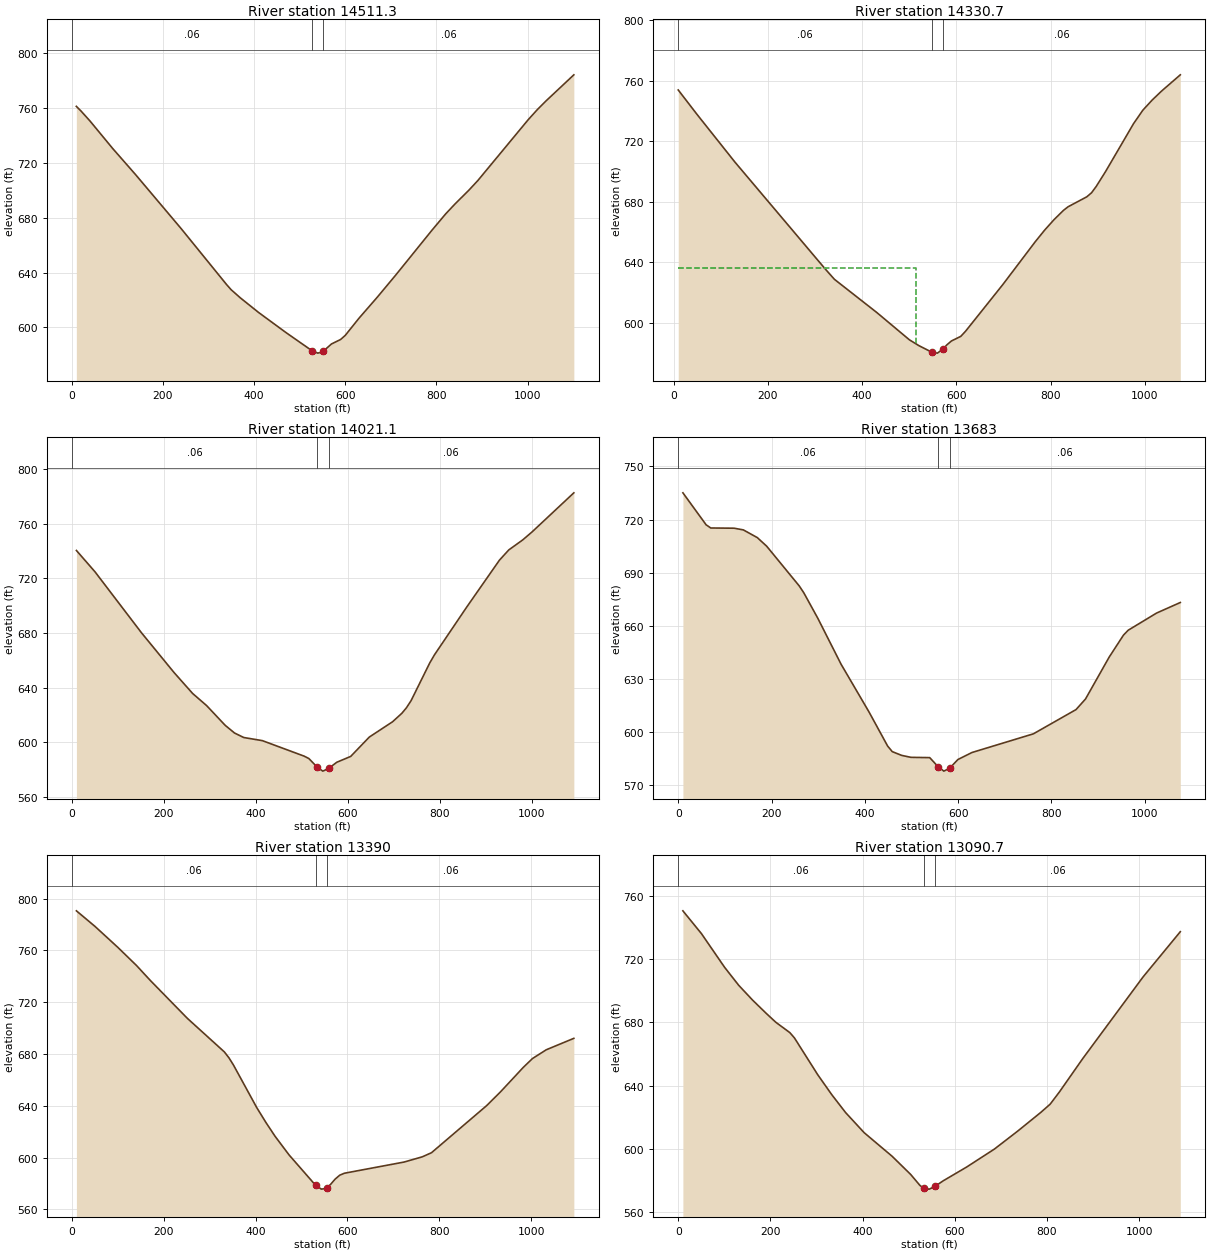
Type RM Length L Ch R = 1 ,14511.3 ,178.9,180.6,178.6
XS GIS Cut Line= 3
     1518802.822      430929.791     1519188.797      430538.551
      1519625.78      430201.833
#Sta/Elev= 30
      10   761.4      20  758.09      40   750.7    89.9  730.57   139.9  711.58
   239.8  672.19   339.7  631.24   349.7  627.49   369.7   621.6   409.7  610.94
   469.6  596.31   527.1  582.95   539.6  581.23   549.6  582.05   552.1  582.73
   569.6  587.91   589.7  591.19   599.7  594.11   629.8  606.62     670  622.01
   710.1  638.01   790.3  671.05   820.4  682.97   840.5  690.08   870.6  700.02
   890.6  707.18  1000.9  751.53    1021  758.94  1041.1  765.62  1101.3  784.41
#Mann= 3 , 0 , 0
       0     .06       0   527.1    .045       0   552.1     .06       0
Bank Sta=527.1,552.1
XS Rating Curve= 0 ,0
Exp/Cntr=0.3,0.1

Type RM Length L Ch R = 1 ,14330.7 ,305.2,309.6,314.3
XS GIS Cut Line= 4
     1518885.358      431057.726     1519180.091      430784.988
     1519430.835      430560.638     1519721.169      430389.077
#Sta/Elev= 30
      10  753.89    50.2  737.62   130.5  706.13   321.3  635.75   341.3  628.72
   431.3  606.75   500.5  588.69   520.3   584.9   547.4   580.6   559.9  579.89
   572.4  582.77   579.7  585.28   589.6  587.92   609.4  590.96   619.3  594.23
   698.4   625.1   767.8  653.66   787.6  661.28   807.5  668.19   827.3  674.26
   837.2  676.67   876.9  683.25   886.8  685.88   896.7  690.03   916.6  699.89
   976.1  731.64   995.9  740.56  1015.7  747.26  1035.6  753.19  1075.3  763.91
#Mann= 3 , 0 , 0
      10     .06       0   547.4    .045       0   572.4     .06       0
#XS Ineff= 2 , 0
          513.48  636.02
Permanent Ineff=
       F       F
Bank Sta=547.4,572.4
XS Rating Curve= 0 ,0
Exp/Cntr=0.3,0.1

Type RM Length L Ch R = 1 ,14021.1 ,323.9,338.1,351.9
XS GIS Cut Line= 3
     1519001.893      431233.286     1519460.409      430936.857
     1519922.505      430645.935
#Sta/Elev= 30
    10.1  740.48    50.6  724.83   151.7  680.18   222.4  651.13   262.9  635.76
   293.2  626.93   333.7  612.45   353.9  606.84   374.1  603.52   414.5  601.24
   505.5  589.87   515.7  588.13   533.5  581.91     546  578.91   558.5  580.84
   576.3  585.38   606.7  589.69   647.1  603.84   697.7  615.05   717.9  621.25
     728  625.33   738.1  630.58   778.6  658.12   788.7  663.99   859.5  699.28
   930.2  733.39   950.5  740.88   980.8  748.21    1001  754.03    1092  782.69
#Mann= 3 , 0 , 0
       0     .06       0   533.5    .045       0   558.5     .06       0
Bank Sta=533.5,558.5
XS Rating Curve= 0 ,0
Exp/Cntr=0.3,0.1

Type RM Length L Ch R = 1 ,13683   ,304.4,293,281.8
XS GIS Cut Line= 4
     1519070.116       431440.44     1519518.815      431246.883
     1519729.967      431233.686     1520081.888      431101.716
#Sta/Elev= 30
      10  735.06    59.8  717.01    69.8  715.22   119.7   715.1   139.6  714.14
   169.5  709.79   189.5  704.97   259.3  682.55   269.3  678.58   299.2  664.27
     349  638.37   408.9  611.42   448.8   592.2   458.7  589.04   478.7  586.94
   498.7  585.82     539  585.66   556.8  580.58   569.3  578.04   581.8   579.7
   599.5   584.6   629.7  588.56   761.2  599.08   852.6  612.76   872.9  618.73
   923.7   642.4   954.2  654.74   964.3  657.52  1025.3  667.23  1076.1  673.18
#Mann= 3 , 0 , 0
       0     .06       0   556.8    .045       0   581.8     .06       0
Bank Sta=556.8,581.8
XS Rating Curve= 0 ,0
Exp/Cntr=0.3,0.1

Type RM Length L Ch R = 1 ,13390   ,300.3,299.3,298.2
XS GIS Cut Line= 3
     1519189.981      431763.776     1519663.982      431519.622
     1520163.314      431267.504
#Sta/Elev= 30
    10.1   790.5    50.3  778.55   100.6  762.17   140.8  748.31     171  736.72
   251.5   707.5     332  681.58     342  677.03   352.1   671.3   402.4  638.66
   422.5  627.08   442.6  616.33   472.8  602.06   530.7  578.54   543.2  575.62
   553.2  576.07   555.7  576.87   563.2  579.26   573.1  583.34   583.1  586.37
   593.1  587.88     723  596.51   762.9  600.57   782.9  603.75   902.8  640.08
   932.7  650.61   982.7  669.66  1002.7  676.47  1032.6  683.22  1092.6  692.04
#Mann= 3 , 0 , 0
       0     .06       0   530.7    .045       0   555.7     .06       0
Bank Sta=530.7,555.7
XS Rating Curve= 0 ,0
Exp/Cntr=0.3,0.1

Type RM Length L Ch R = 1 ,13090.7 ,315.4,317.7,319.8
XS GIS Cut Line= 2
     1519356.052      432034.306     1520306.237      431502.026
#Sta/Elev= 30
    10.1  750.58    50.4  736.13   100.8  714.76   131.1  703.49   161.4  694.05
   191.6  685.49   211.8  680.03     242  673.54   252.1  670.15   302.5  646.92
   332.8  634.35     363  622.94   403.4  610.17   463.9  595.29   504.2  583.77
   524.4   576.8   532.1  575.15   534.5  574.63   544.6  574.48   557.1  576.24
   574.8  579.75   625.2  588.38   685.7   599.8   736.2  611.15   786.6  623.06
   806.8  628.25   826.9  635.99   877.3  657.01  1008.4  708.78  1089.1  737.37
#Mann= 3 , 0 , 0
       0     .06       0   532.1    .045       0   557.1     .06       0
Bank Sta=532.1,557.1
XS Rating Curve= 0 ,0
Exp/Cntr=0.3,0.1

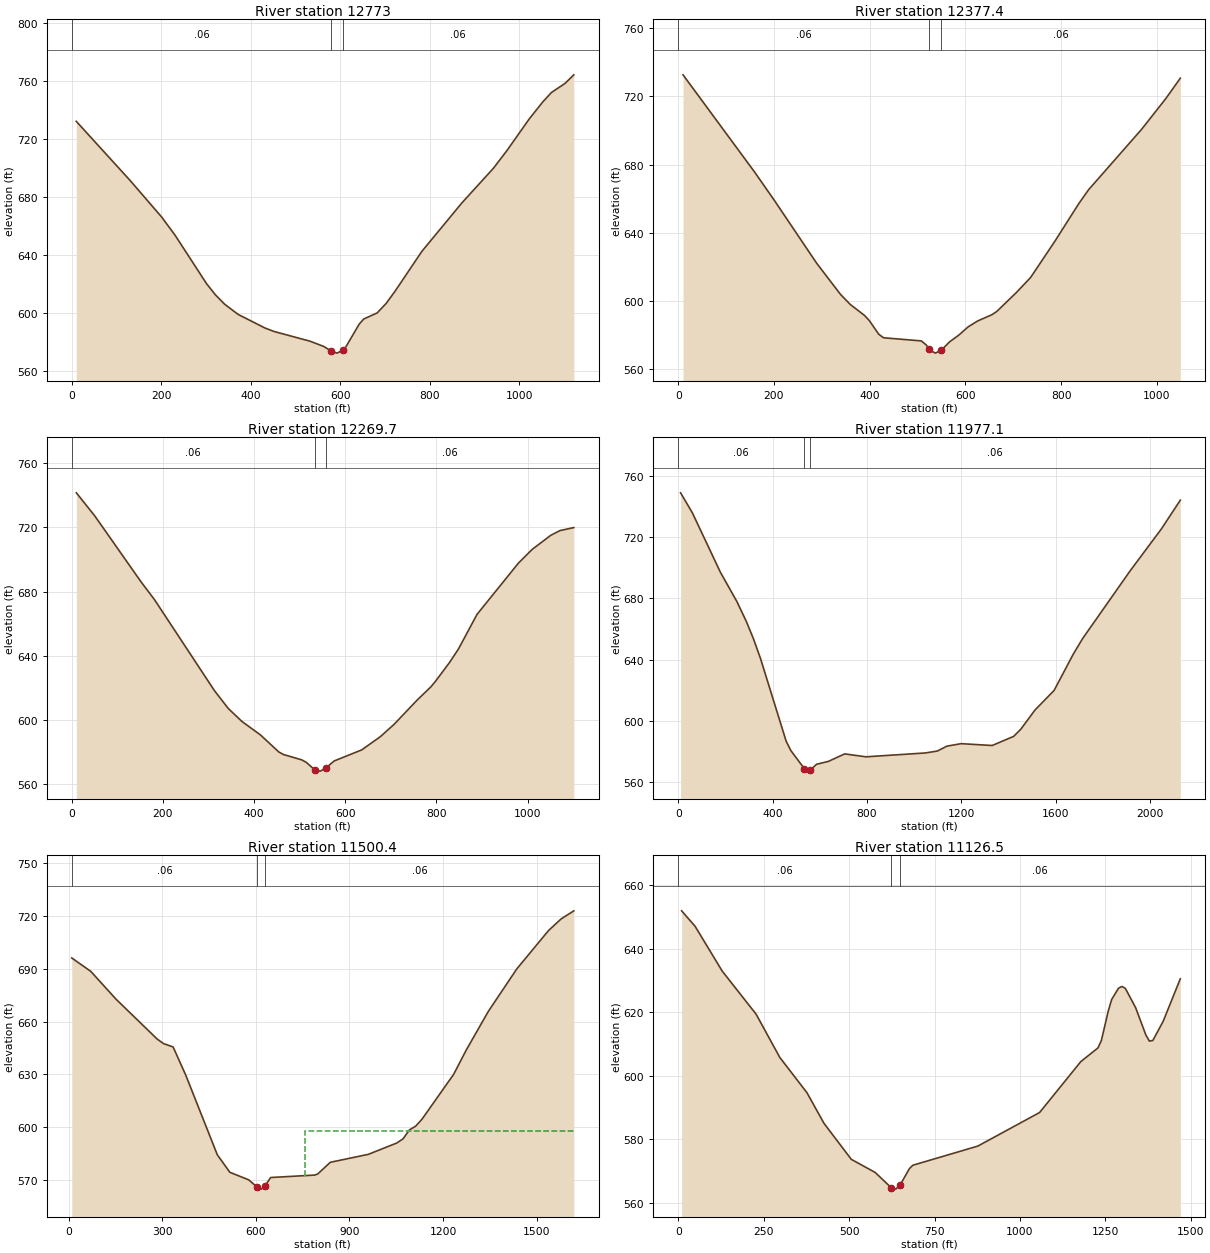
Type RM Length L Ch R = 1 ,12773   ,384.9,395.5,406.5
XS GIS Cut Line= 3
     1519449.477      432235.724     1519995.062      432031.455
     1520487.418      431811.058
#Sta/Elev= 30
      10  732.21   130.6  691.32   200.9  666.18     231  653.59   301.3  620.17
   321.4   612.4   341.5   606.1   371.6  599.05   431.9  589.62     452  587.26
   532.3  580.56   562.5  577.01   580.1  573.76   592.6  572.32   605.1  574.15
   612.5  576.61   642.5   592.4   652.5  595.85   682.5  600.05   702.4  606.54
   722.4  614.99   782.4  642.51   872.3   676.1   942.2  699.79   972.2   711.9
  1022.1  733.74  1052.1  745.41  1072.1  752.13    1102  758.27    1122  764.26
#Mann= 3 , 0 , 0
       0     .06       0   580.1    .045       0   605.1     .06       0
Bank Sta=580.1,605.1
XS Rating Curve= 0 ,0
Exp/Cntr=0.3,0.1

Type RM Length L Ch R = 1 ,12377.4 ,105.9,107.7,110.5
XS GIS Cut Line= 4
     1519491.934      432424.616     1519950.727      432421.578
     1520126.952      432415.501      1520540.17      432433.731
#Sta/Elev= 30
      10  732.61   159.6  675.63   199.5   659.6   289.2  622.24   339.1  603.96
   359.1  598.17     389   591.7     399  588.72   418.9  580.64   428.9  578.59
   507.8  576.75   517.6   574.5   524.7     572   527.4  571.05   537.2  569.59
   549.7  571.32   566.6  576.15   586.2  580.18   605.7     585   625.3  588.41
   655.3   592.1   665.4     594   705.8  604.93     736  613.87   786.5     635
   836.9  657.23   857.1  665.27     968  700.71  1018.5   718.7  1048.8  730.64
#Mann= 3 , 0 , 0
       0     .06       0   524.7    .045       0   549.7     .06       0
Bank Sta=524.7,549.7
XS Rating Curve= 0 ,0
Exp/Cntr=0.3,0.1

Type RM Length L Ch R = 1 ,12269.7 ,288.5,292.7,295.8
XS GIS Cut Line= 3
     1519488.022      432509.398     1520032.964       432526.55
     1520587.773      432566.585
#Sta/Elev= 30
    10.1  741.37    50.5  727.01   151.4  686.25   181.7  674.85     313  618.36
   343.3  607.26   373.6  599.12     414   590.8   454.3  580.19   464.4  578.62
   504.8  575.27   514.9  573.67   532.7  569.17   545.2  568.29   557.7  570.24
   575.6  574.61   636.2   581.5   676.7  589.66     707  597.35   757.6  612.44
   787.9  620.72   798.1  624.22   828.4   635.7   848.6  644.36   889.1  665.78
   980.1  697.72  1010.4  706.27  1050.9  714.95  1071.1  717.89  1101.5  719.76
#Mann= 3 , 0 , 0
       0     .06       0   532.7    .045       0   557.7     .06       0
Bank Sta=532.7,557.7
XS Rating Curve= 0 ,0
Exp/Cntr=0.3,0.1

Type RM Length L Ch R = 1 ,11977.1 ,471.8,476.7,481.6
XS GIS Cut Line= 4
     1519474.825      432685.358     1519888.331      432795.334
     1520200.661      432852.521     1521501.694      433322.846
#Sta/Elev= 30
      10  748.89    59.7  735.91   179.1  696.98   248.8  677.92   288.6  665.01
   318.4  653.85   348.3  641.05   457.6  586.84   477.5   580.7   534.5  568.97
     547   567.3   559.5  567.96   586.6  571.77   636.3  573.63   705.7  578.54
   795.9  576.64  1048.3  579.16  1098.8  580.42  1139.2   583.6  1199.8  585.22
  1331.1  584.02    1422  589.96  1452.3  594.61  1512.9  607.21  1593.6  619.94
  1674.4  643.47  1714.8  653.85  1916.8  698.14  2048.1  725.23  2128.8   744.1
#Mann= 3 , 0 , 0
       0     .06       0   534.5    .045       0   559.5     .06       0
Bank Sta=534.5,559.5
XS Rating Curve= 0 ,0
Exp/Cntr=0.3,0.1

Type RM Length L Ch R = 1 ,11500.4 ,365.8,373.9,382.7
XS GIS Cut Line= 4
     1519454.179      432994.173     1519820.697      433230.698
     1520198.736      433368.167     1520934.195      433629.358
#Sta/Elev= 30
    10.1   696.1      71   688.5   152.2  672.67     284  650.05   304.3   647.5
   334.8  645.62   375.3  629.65   476.4  584.45   516.7  574.49     577  570.22
   604.7  566.03   617.2  564.95   629.7  566.87   647.4  571.54   788.2  572.91
   798.2  573.54   838.5  580.17   960.1  584.67  1051.3  591.09  1071.6  593.48
  1091.9  598.52  1112.1  600.69  1132.4  604.64  1233.8  630.09  1274.3  643.91
  1345.3   665.9  1436.5  689.98  1537.8  711.65  1578.4  718.29  1618.9  722.84
#Mann= 3 , 0 , 0
    10.1     .06       0   604.7    .045       0   629.7     .06       0
#XS Ineff= 2 , 0
                          757.25          598.02
Permanent Ineff=
       F       F
Bank Sta=604.7,629.7
XS Rating Curve= 0 ,0
Exp/Cntr=0.3,0.1

Type RM Length L Ch R = 1 ,11126.5 ,666.5,660,652.7
XS GIS Cut Line= 4
     1519390.795      433119.033     1519690.101      433347.546
     1519944.419      433718.713     1520528.662      433986.777
#Sta/Elev= 30
     9.9  651.88    49.5  646.99   128.8  632.89   227.9  619.34   297.3  605.71
   376.6  594.63   426.6  584.96   506.5  573.63   576.5  569.49     624  564.63
   636.5  564.25     649  565.47   676.5   570.7   686.5  571.77   876.7   577.8
  1057.5  588.37    1178  604.39  1228.3  608.71  1238.3  611.05  1258.4  620.31
  1268.4  623.95  1288.5  627.52  1298.6  628.07  1308.6  627.44  1338.7  621.35
  1368.9  612.68  1378.9  610.86    1389  611.07  1419.1  617.09  1469.3  630.48
#Mann= 3 , 0 , 0
       0     .06       0     624    .045       0     649     .06       0
Bank Sta=624,649
XS Rating Curve= 0 ,0
Exp/Cntr=0.3,0.1