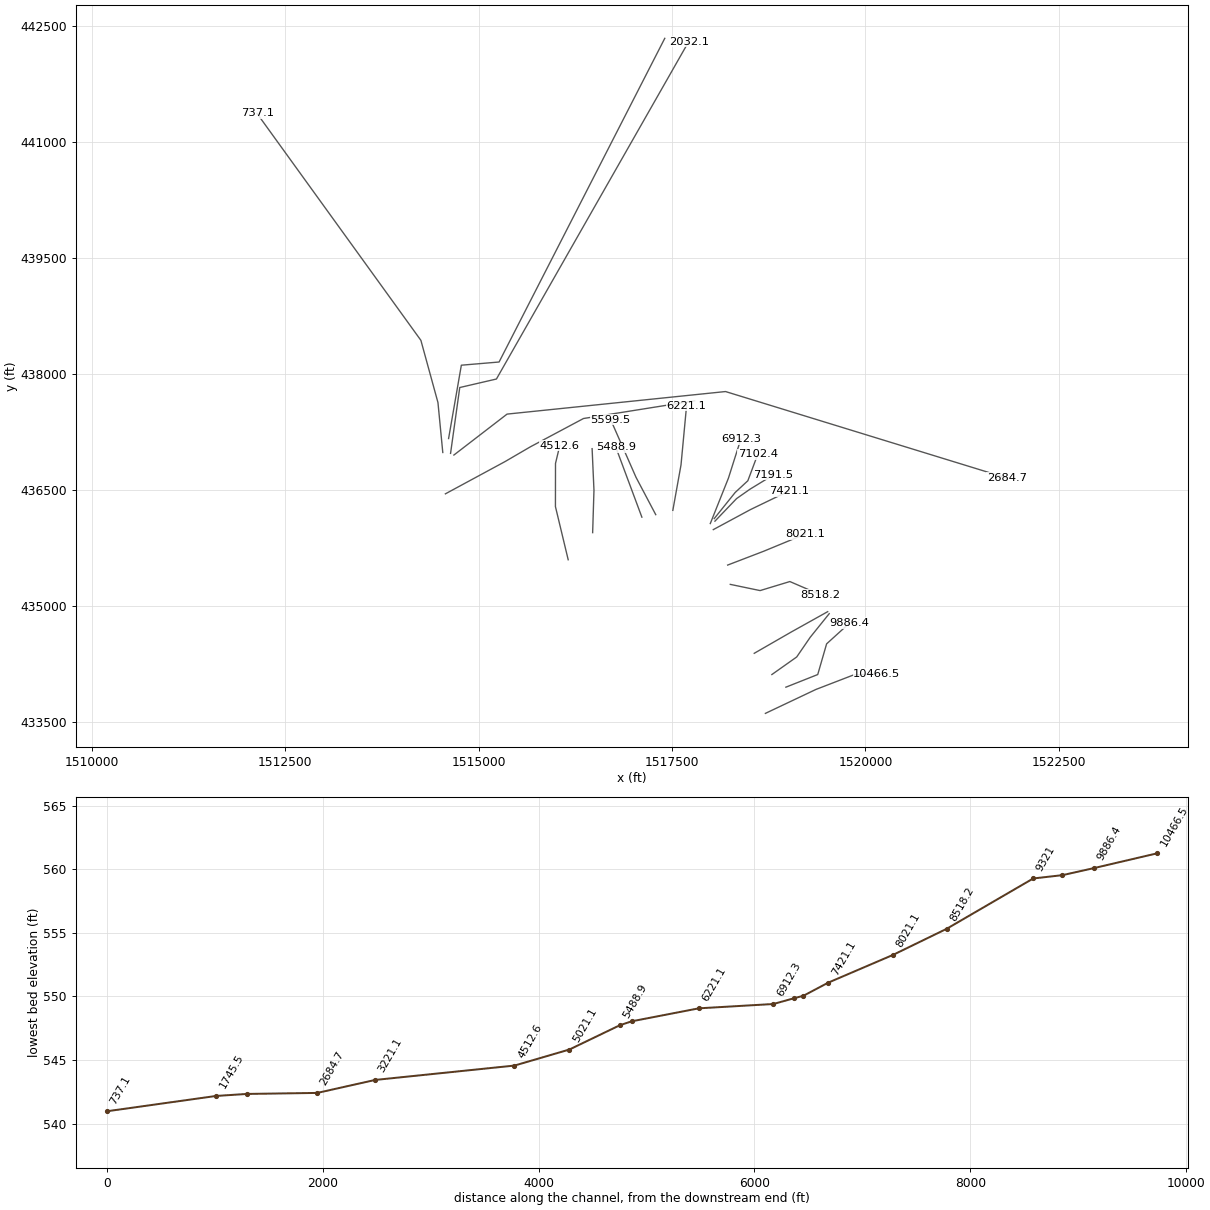
HEC-RAS study HURICANCR.prj: HURICANCR

--- HURICANCR.g01 (geometry) --- (continued)

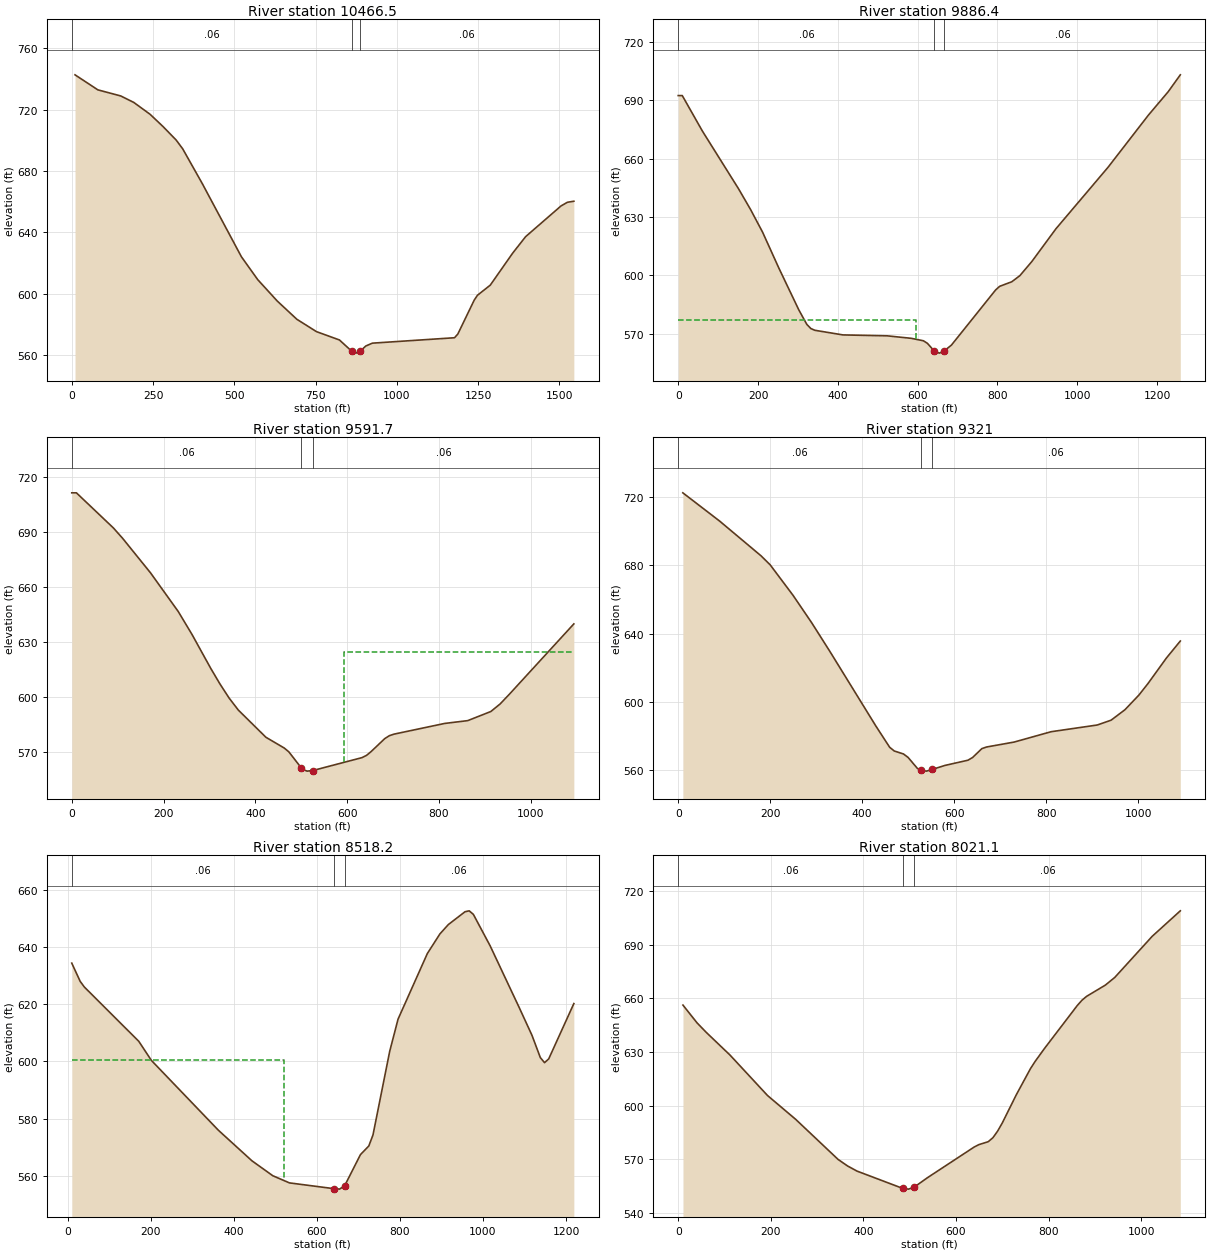
Type RM Length L Ch R = 1 ,10466.5 ,558.4,580.1,600.9
XS GIS Cut Line= 4
     1518707.198      433615.611     1519360.176      433924.916
     1519841.317      434110.499     1520147.314      434126.986
#Sta/Elev= 30
      10  742.67    80.3  732.87   150.5  728.91   190.7  724.69   240.8  716.97
     281   708.9   321.1  700.17   341.2  694.46   401.4  671.83   521.8  624.11
     572  609.18   632.2  595.21   692.4  583.33   752.9  575.25   823.6  569.81
   861.7  562.42   874.2  561.24   886.7  562.33   904.5  565.87   924.8  567.74
  1177.6  571.27  1187.7  573.66  1238.2   595.8  1248.1  598.95  1287.6  605.57
  1356.8  626.51  1396.4  637.18  1505.1  657.17  1524.9  659.59  1544.7  660.26
#Mann= 3 , 0 , 0
       0     .06       0   861.7    .045       0   886.7     .06       0
Bank Sta=861.7,886.7
XS Rating Curve= 0 ,0
Exp/Cntr=0.3,0.1

Type RM Length L Ch R = 1 ,9886.4  ,320,294.7,269.2
XS GIS Cut Line= 4
     1518971.974      433954.379     1519383.869      434117.814
     1519498.659       434514.59     1519796.836      434784.754
#Sta/Elev= 30
       0  692.32    10.1  692.32    60.4  674.15   151.1  644.49   181.3  633.83
   211.5  622.17   251.8  603.94   302.1  582.35   322.3  574.85   332.4  572.71
   342.4  571.82   412.9  569.44   523.7  568.97   584.2  567.69   614.4  566.44
   624.5  565.14   642.2  561.08   654.7  560.09   667.2  561.29   684.9  564.24
   795.7  592.56   805.8   594.4     836  596.72   856.2  599.84   886.4  607.13
   946.7  623.92  1077.5  655.54  1178.1  682.17  1228.4  694.37  1258.5  702.97
#Mann= 3 , 0 , 0
       0     .06       0   642.2    .045       0   667.2     .06       0
#XS Ineff= 2 , 0
          595.39     577
Permanent Ineff=
       F       F
Bank Sta=642.2,667.2
XS Rating Curve= 0 ,0
Exp/Cntr=0.3,0.1

Type RM Length L Ch R = 1 ,9591.7  ,283,270.7,258.3
XS GIS Cut Line= 4
     1518790.948      434117.842     1519111.865        434344.9
     1519286.546      434599.436     1519532.309      434904.779
#Sta/Elev= 30
       0  711.32    10.1  711.32    90.7  692.16   110.9  686.47   171.4  667.73
   231.8  646.65   262.1  634.01   302.4  615.74   322.6  607.18   342.7  599.41
   362.9  592.82     423  577.99   462.8  572.14   472.8  570.08   500.1  561.27
   502.7  560.54   512.6  559.53   525.1  559.85   632.1  566.88   642.1  568.12
     652  570.16   681.9  577.27   691.9  578.86   701.8  579.69   812.4  585.54
   862.6  587.07   912.9  592.04     933  596.12   953.1   601.4  1093.8  639.83
#Mann= 3 , 0 , 0
       0     .06       0   500.1    .045       0   525.1     .06       0
#XS Ineff= 2 , 0
                          593.91           624.4
Permanent Ineff=
       F       F
Bank Sta=500.1,525.1
XS Rating Curve= 0 ,0
Exp/Cntr=0.3,0.1

Type RM Length L Ch R = 1 ,9321    ,808.8,802.8,803.5
XS GIS Cut Line= 3
     1518562.856       434392.31     1519039.304      434666.579
     1519512.543      434930.661
#Sta/Elev= 30
      10  722.64      90  706.06   179.9   685.7   199.9  680.37   249.9  662.37
   289.9  646.49   329.9  629.47   429.8  585.72   459.8  573.25   469.8  571.09
   489.8  569.34   499.8  567.32   519.8  560.94   527.3  559.73   539.8  559.27
   552.3  560.28   579.9  562.61     630  565.68   640.1  567.28   660.1  572.47
   670.2  573.42   730.4  576.33   810.7   582.4     911  586.34   941.1  589.16
   971.3   595.3  1001.4  603.84  1021.4  610.68  1061.6  625.71  1091.7  635.64
#Mann= 3 , 0 , 0
       0     .06       0   527.3    .045       0   552.3     .06       0
Bank Sta=527.3,552.3
XS Rating Curve= 0 ,0
Exp/Cntr=0.3,0.1

Type RM Length L Ch R = 1 ,8518.2  ,495.9,497.1,499.5
XS GIS Cut Line= 4
     1518253.256      435283.616     1518638.464      435203.377
     1519023.377      435320.226     1519411.909      435152.397
#Sta/Elev= 30
    10.1  634.41    30.3  628.04    40.4  626.04   171.5  607.04   201.8  600.36
   363.2  575.91   443.8  565.24     494  560.01   534.3  557.49   642.4  555.45
   654.9  555.31   667.4  556.55   705.2  567.39   725.3  570.41   735.4  574.29
   775.6  603.52   795.7  614.79   866.3  637.77   896.5  644.62   916.7  647.89
     957  652.39     967  652.71   977.1  651.46  1017.4  640.48    1088  618.69
  1118.2  609.14  1138.3  601.35  1148.4  599.57  1158.5  600.89    1219  620.25
#Mann= 3 , 0 , 0
    10.1     .06       0   642.4    .045       0   667.4     .06       0
#XS Ineff= 2 , 0
          520.56  600.66
Permanent Ineff=
       F       F
Bank Sta=642.4,667.4
XS Rating Curve= 0 ,0
Exp/Cntr=0.3,0.1

Type RM Length L Ch R = 1 ,8021.1  ,596.1,600,602
XS GIS Cut Line= 3
     1518219.183      435533.303     1518683.612      435711.445
     1519226.055      435935.508
#Sta/Elev= 30
    10.2  656.15    40.6  646.22    60.9   640.8   111.7  628.25   192.9  605.58
   253.8  592.24   345.2  569.88   365.5  566.24   385.8  563.37   484.9  553.66
   497.4  553.26   509.9  554.42   537.9  559.59   639.1  576.79   649.2  578.13
   669.4  579.77   679.6  582.01   689.7  585.67   699.8  590.23   730.2  606.06
   760.5  620.53   770.6  624.59   790.9  631.87   861.7  655.88   871.8  658.83
   881.9  661.03   922.4  667.32   942.7  671.59  1023.6   694.6  1084.3  708.85
#Mann= 3 , 0 , 0
       0     .06       0   484.9    .045       0   509.9     .06       0
Bank Sta=484.9,509.9
XS Rating Curve= 0 ,0
Exp/Cntr=0.3,0.1

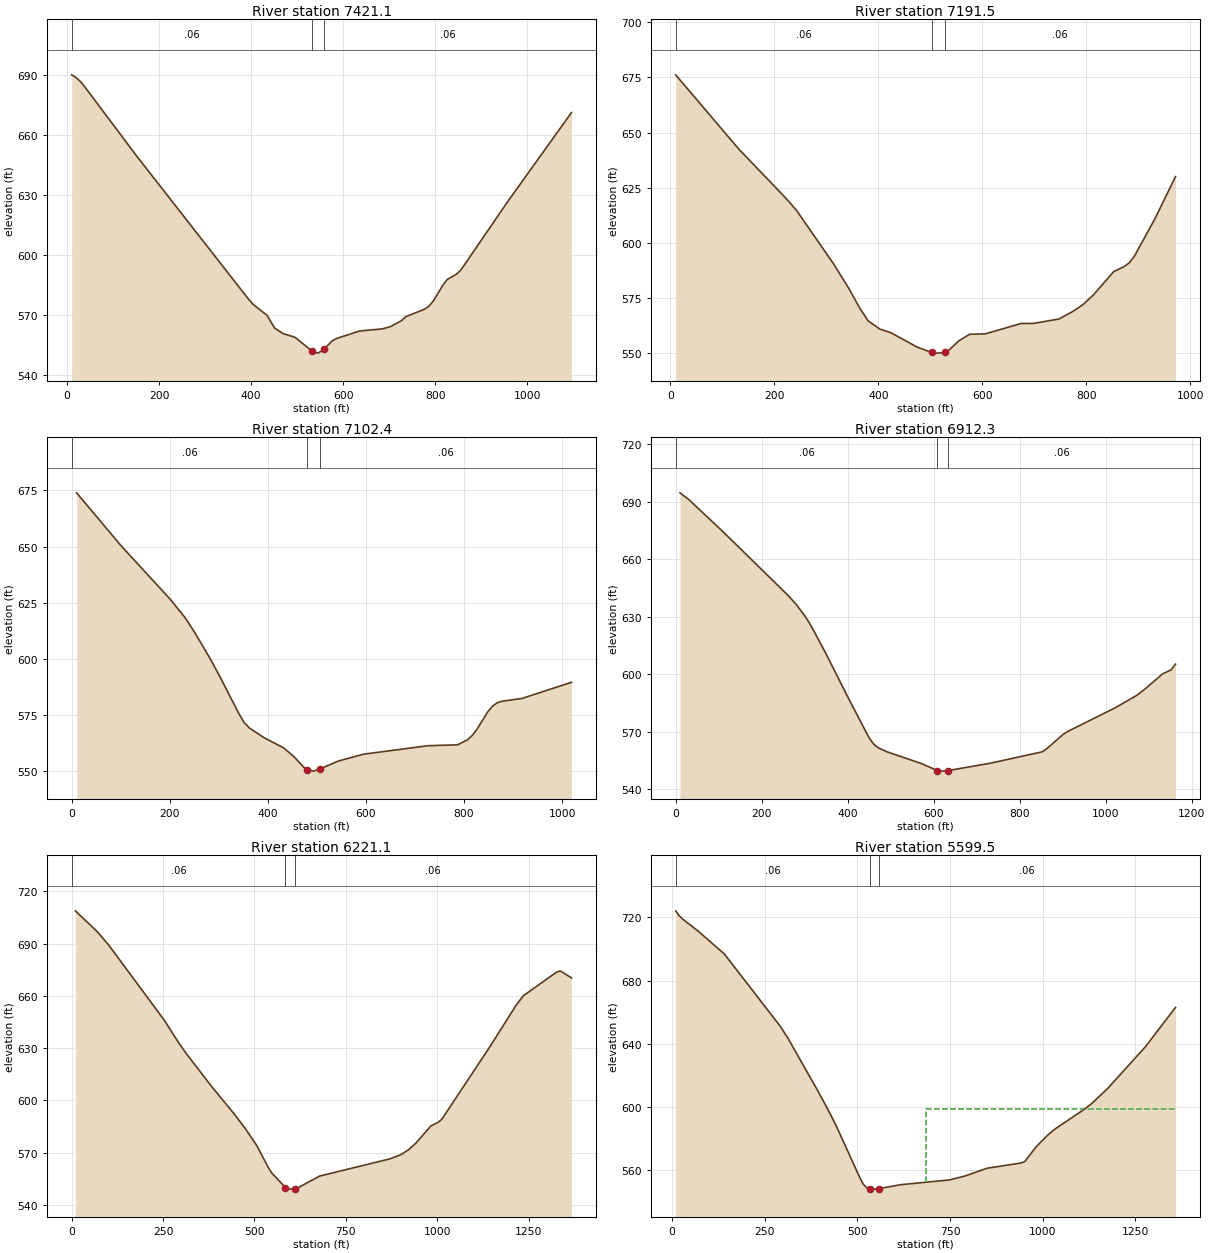
Type RM Length L Ch R = 1 ,7421.1  ,226.7,229.6,234.1
XS GIS Cut Line= 3
       1518033.5      435991.719     1518514.013      436250.759
     1519009.605      436490.237
#Sta/Elev= 30
    10.1  690.31    20.2  688.86    30.3  686.69    40.4  683.75   151.6  649.62
   394.3  578.13   404.4  575.48   434.7     570  451.08  563.65   469.1  560.88
   495.3  559.04   533.4  551.93   545.9  551.08   558.4  553.03   575.9  557.15
   585.9  558.42     636  562.15  685.33  563.21  703.35  564.38  726.87   567.3
     736  569.28   776.1  572.97   786.1  574.49   796.1  577.17   816.1  584.81
   826.1  587.92   846.1  590.54   856.1  592.71   956.2   626.4  1096.3  671.44
#Mann= 3 , 0 , 0
    10.1     .06       0   533.4    .045       0   558.4     .06       0
Bank Sta=533.4,558.4
XS Rating Curve= 0 ,0
Exp/Cntr=0.3,0.1

Type RM Length L Ch R = 1 ,7191.5  ,85,89,92.8
XS GIS Cut Line= 4
     1518054.787      436101.037     1518334.317      436392.721
     1518507.504      436514.255      1518811.34      436699.595
#Sta/Elev= 30
    10.1  676.16   131.3  642.58   222.2  620.24   242.4   614.8   313.1  590.75
   343.4   579.3   363.6  570.68  380.28  564.66  402.76  560.95  423.88  559.32
   474.5   552.8   502.3  550.34   514.8  550.05   527.3  550.36     535  551.26
   555.1  555.67   575.3  558.58   605.5  558.78   674.9  563.51  697.05  563.48
  746.86  565.48   773.8   568.9   793.5  572.02   813.3  576.34   852.8  587.01
   872.6  589.23   882.5  590.97   892.4  593.96   931.9  610.93   971.5  630.01
#Mann= 3 , 0 , 0
    10.1     .06       0   502.3    .045       0   527.3     .06       0
Bank Sta=502.3,527.3
XS Rating Curve= 0 ,0
Exp/Cntr=0.3,0.1

Type RM Length L Ch R = 1 ,7102.4  ,176.8,190.1,204.6
XS GIS Cut Line= 4
     1518045.672      436134.459     1518316.087      436471.718
     1518480.158      436623.636      1518607.77      436963.933
#Sta/Elev= 30
    10.1  673.96   100.5  650.43   201.1  626.46   231.2  618.32   251.3  611.56
   281.5  600.38   301.6   592.3   341.8  575.17   351.9  571.53   361.9  569.18
   392.1  564.79   432.3  560.22   452.6  556.47   472.9  551.67   480.8  550.45
   493.3  549.85   505.8  550.77   544.1  554.37   594.9  557.39   726.6  561.19
   787.1  561.58   807.3  563.85   817.4  565.86   827.5  568.86   847.7  576.04
   857.8  578.75   867.9  580.37     878  581.03   918.4  582.27  1019.3  589.46
#Mann= 3 , 0 , 0
       0     .06       0   480.8    .045       0   505.8     .06       0
Bank Sta=480.8,505.8
XS Rating Curve= 0 ,0
Exp/Cntr=0.3,0.1

Type RM Length L Ch R = 1 ,6912.3  ,686.4,691.2,697.2
XS GIS Cut Line= 3
     1517994.689      436070.303      1518228.84      436656.644
     1518389.772      437162.602
#Sta/Elev= 30
      10  694.69    30.1  691.27   110.2  674.38   260.6  641.31   280.6  636.38
   300.7  630.28   310.7  626.84   320.7  622.82   350.8  610.16   400.9  587.83
     441  570.55     451   566.4     461  563.38     471  561.62   491.1  559.51
   571.2  553.37   608.8  549.67   621.3   549.4   633.8   549.7   731.5  553.52
   851.8  559.45   861.8  560.87   901.8  568.71   911.9  570.12  1022.1  582.46
  1072.1  588.95  1092.2  592.41  1132.2  600.16  1152.3  602.31  1162.3  605.25
#Mann= 3 , 0 , 0
       0     .06       0   608.8    .045       0   633.8     .06       0
Bank Sta=608.8,633.8
XS Rating Curve= 0 ,0
Exp/Cntr=0.3,0.1

Type RM Length L Ch R = 1 ,6221.1  ,603.3,621.6,636.2
XS GIS Cut Line= 3
     1517510.276      436240.692     1517615.982      436828.533
     1517687.991      437594.927
#Sta/Elev= 30
    10.1  708.85    70.9  696.72   101.2  689.23   253.1  646.12   293.6  632.83
   313.8  626.79   384.7  607.49   445.4  592.02   475.8  583.57   506.2  574.13
   536.5  562.01   546.7  558.47   584.8  549.96   597.3  549.06   609.8  549.25
   617.5  549.69   678.3  556.57   870.7  566.44   901.1  568.92   921.4  571.66
   941.6   575.5   982.2   585.3  1002.4  587.44  1012.5  589.19  1144.2  630.95
  1215.1  654.51  1235.4  660.12  1326.5  673.68  1336.7  674.31    1367  670.36
#Mann= 3 , 0 , 0
       0     .06       0   584.8    .045       0   609.8     .06       0
Bank Sta=584.8,609.8
XS Rating Curve= 0 ,0
Exp/Cntr=0.3,0.1

Type RM Length L Ch R = 1 ,5599.5  ,114.2,110.5,108.2
XS GIS Cut Line= 3
     1517289.059      436185.243     1517034.355        436667.8
     1516707.063      437411.576
#Sta/Elev= 30
    10.1  724.12    20.2   720.9    30.3  718.67    70.7   711.3   141.5   696.8
     293  650.85   313.2  643.42   394.1  610.03   424.4  596.78   444.6  587.37
   505.2  556.13   515.3  551.47   525.4   548.9   533.2  548.28   545.7  548.04
   558.2  548.36   616.8  550.83   748.8  553.87   789.4  556.24   850.4  561.27
   941.8  564.57     952  565.55   982.4  574.82  1012.9  582.05  1033.2  586.06
  1114.5   598.9  1134.8  602.72  1175.4  611.74    1277  638.08  1358.3  663.01
#Mann= 3 , 0 , 0
    10.1     .06       0   533.2    .045       0   558.2     .06       0
#XS Ineff= 2 , 0
                          684.79          598.99
Permanent Ineff=
       F       F
Bank Sta=533.2,558.2
XS Rating Curve= 0 ,0
Exp/Cntr=0.3,0.1

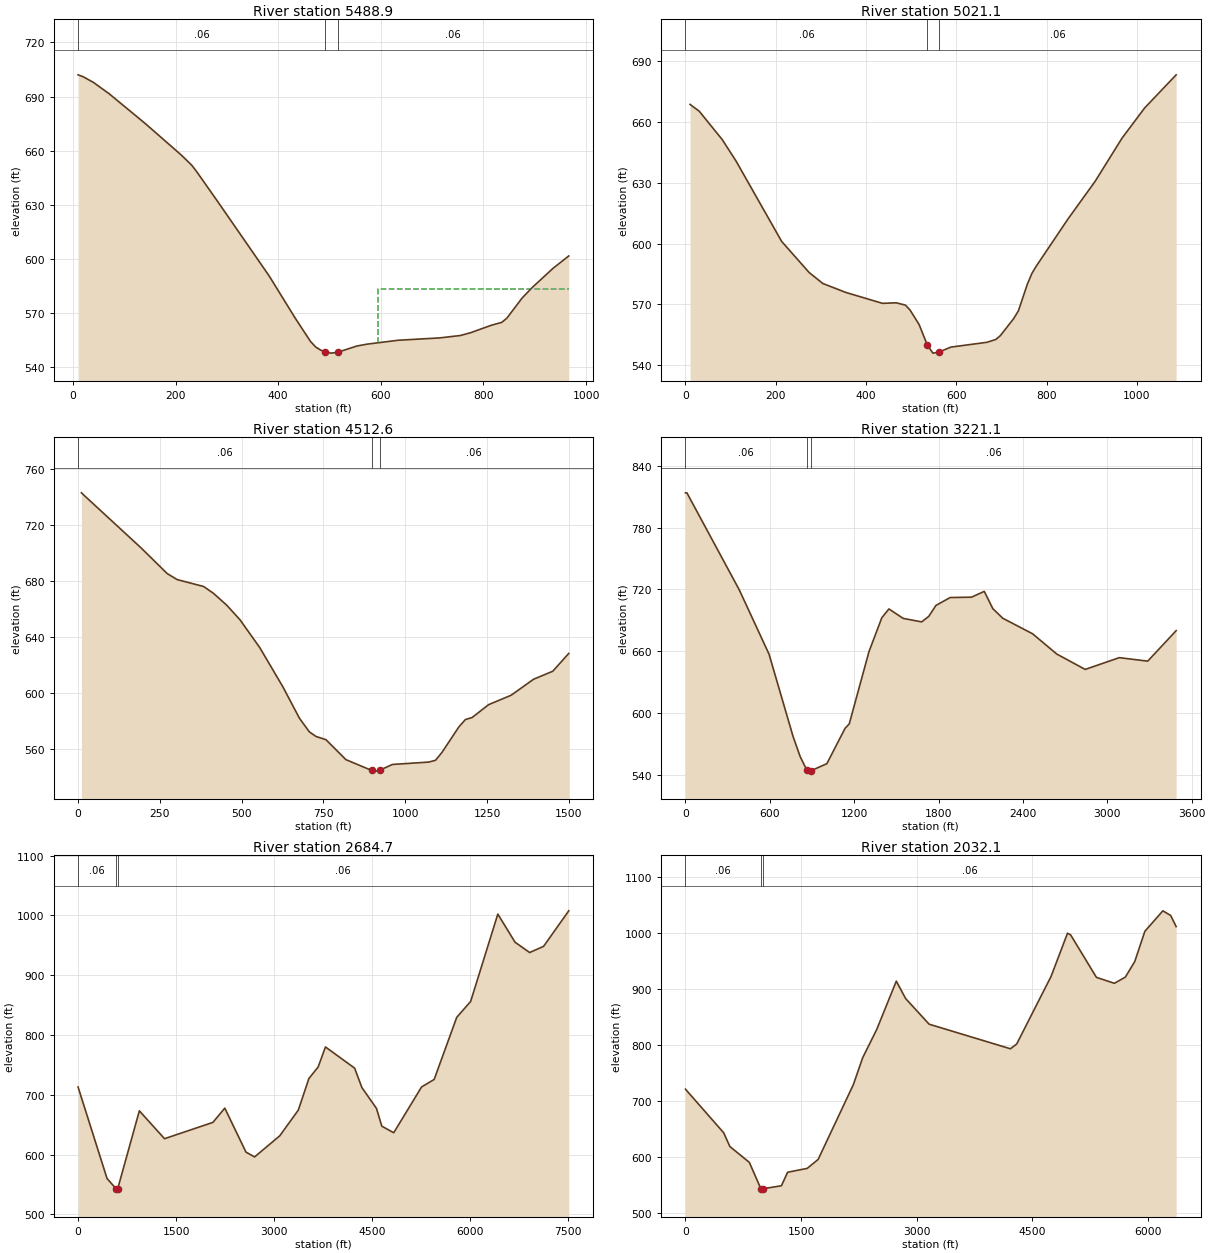
Type RM Length L Ch R = 1 ,5488.9  ,478.5,467.8,459.3
XS GIS Cut Line= 2
     1517109.856       436152.69     1516772.597      437058.122
#Sta/Elev= 30
    10.1  702.04    20.1  700.98    40.3  697.79    70.5  691.58   140.9  675.06
   211.4  657.52   231.5  651.94   241.6  648.21   281.8  631.93   382.5  590.51
   432.8  567.32     463  554.22     473  551.15   483.1  549.36   490.7  548.51
   503.2  547.73   515.7  548.19   553.6  551.69   573.7  552.73   634.1  554.87
   714.6  556.17   754.8  557.49     775  559.05   815.2  563.17   835.4  564.77
   845.4  567.04   875.6  578.38   895.8  584.33     936  594.86   966.2  601.61
#Mann= 3 , 0 , 0
    10.1     .06       0   490.7    .045       0   515.7     .06       0
#XS Ineff= 2 , 0
                          594.59          583.01
Permanent Ineff=
       F       F
Bank Sta=490.7,515.7
XS Rating Curve= 0 ,0
Exp/Cntr=0.3,0.1

Type RM Length L Ch R = 1 ,5021.1  ,508.1,508.5,506.7
XS GIS Cut Line= 3
     1516473.328      435952.583     1516490.419      436500.271
     1516466.454      437038.588
#Sta/Elev= 30
    10.1  668.77    30.4  665.42    81.2  651.43   111.6  640.93   213.1  601.02
     274  585.65   304.4  580.22   355.2  575.82   436.3  570.43   466.8  570.69
   487.1  569.55   497.2  567.19   517.5  559.96   535.5  549.88     548  545.82
   560.5  546.25   587.9   548.8   667.7  551.17   687.7  552.61   697.6  554.51
   727.6  563.09   737.5   566.8   757.5  580.08   767.5  585.31   777.5  588.99
   847.3  612.15   907.2  630.69   967.1  652.14    1017     667  1086.8  683.38
#Mann= 3 , 0 , 0
       0     .06       0   535.5    .045       0   560.5     .06       0
Bank Sta=535.5,560.5
XS Rating Curve= 0 ,0
Exp/Cntr=0.3,0.1

Type RM Length L Ch R = 1 ,4512.6  ,1316.9,1291.5,1269.5
XS GIS Cut Line= 4
     1516157.149      435602.037     1515992.186      436289.382
      1515993.07      436847.566     1516047.723      437075.798
#Sta/Elev= 30
    10.1  743.18   191.9  704.02   272.6  685.52   302.9  681.26   383.7  676.33
     414  671.42   454.4  662.98   494.8  652.62   555.4  632.69   626.1  604.68
   676.6   582.3   706.9  572.58   727.2  569.31   757.6  566.99   818.5  552.77
   897.3  545.06   909.8  544.56   922.3  545.25   960.6  549.31  1072.2  551.03
  1092.5   552.3  1112.8  558.12  1163.6  576.04  1183.9   581.4  1204.2   582.8
  1254.9  592.02  1323.7  598.73  1392.2  610.15  1450.8  615.84  1499.7  628.57
#Mann= 3 , 0 , 0
       0     .06       0   897.3    .045       0   922.3     .06       0
Bank Sta=897.3,922.3
XS Rating Curve= 0 ,0
Exp/Cntr=0.3,0.1

Type RM Length L Ch R = 1 ,3221.1  ,535.7,536.4,532.7
XS GIS Cut Line= 5
     1514569.383      436454.345     1515340.188      436871.169
      1515667.09      437061.687      1516355.06      437428.424
      1517792.56       437657.59
#Sta/Elev= 30
       0  813.98    10.1  813.98   382.7  719.65   594.3  657.18   765.5  577.02
   815.9   557.5   863.3  544.41   876.3  543.43   889.3  543.63  1005.7   550.7
  1135.2  585.05    1165   589.4  1305.3  659.65  1396.4  692.54    1447  701.11
  1548.3  691.92  1679.9  688.52  1730.5  693.89  1781.1  704.47  1882.4   712.2
  2034.3  712.52  2125.2  718.19  2185.9  701.41  2256.7  692.05  2468.9  676.95
  2640.8  657.26    2843   642.3  3085.6  653.75  3287.7  650.34  3489.9  680.01
#Mann= 3 , 0 , 0
       0     .06       0   863.3    .045       0   889.3     .06       0
Bank Sta=863.3,889.3
XS Rating Curve= 0 ,0
Exp/Cntr=0.3,0.1

Type RM Length L Ch R = 1 ,2684.7  ,663.7,652.6,641.6
XS GIS Cut Line= 4
     1514679.358      436956.106     1515366.703      437485.362
     1518191.372      437777.001     1521830.361      436658.618
#Sta/Elev= 30
       0  713.12   443.8  560.14   582.6  543.05   595.1  542.41   607.6  543.27
   938.5  673.32  1323.9  626.73  2064.2  653.94  2246.8  677.85  2571.3  604.31
  2703.2  596.24  3088.5  631.55  3372.5  674.49  3534.8   727.3  3676.8   746.7
  3788.4  780.11  4235.1  744.68  4346.8  712.13  4570.1  677.28  4651.3  647.64
    4834  636.69  5260.4  713.24  5453.3  725.78  5798.5  829.61  6011.7  856.17
  6427.9 1002.27  6691.8   955.2  6915.2  937.98  7128.4  948.28  7514.2 1007.69
#Mann= 3 , 0 , 0
       0     .06       0   582.6    .045       0   607.6     .06       0
Bank Sta=582.6,607.6
XS Rating Curve= 0 ,0
Exp/Cntr=0.3,0.1

Type RM Length L Ch R = 1 ,2032.1  ,290.6,286.5,282.5
XS GIS Cut Line= 4
      1514636.11      436977.501     1514754.966      437829.034
     1515229.234      437939.009     1517716.048      442302.876
#Sta/Elev= 30
       0   720.9   495.6  643.05   576.6  618.41   829.4  590.09   979.1  542.86
   991.6  542.33  1004.1     543  1245.2  548.34  1326.4   572.5    1580  579.37
  1722.1  595.37  2178.7  728.85  2300.4  777.13  2483.1  827.74  2736.8  913.92
  2858.5   882.7  3162.9  837.01  4218.2  793.07  4299.4   801.6  4745.8  922.43
  4958.9  999.51  4999.5  996.61  5334.4  920.67  5567.7  910.07  5709.8  921.13
  5831.6  948.83  5963.5 1003.05  6196.8 1039.54  6298.3 1031.27  6369.3 1011.31
#Mann= 3 , 0 , 0
       0     .06       0   979.1    .045       0  1004.1     .06       0
Bank Sta=979.1,1004.1
XS Rating Curve= 0 ,0
Exp/Cntr=0.3,0.1

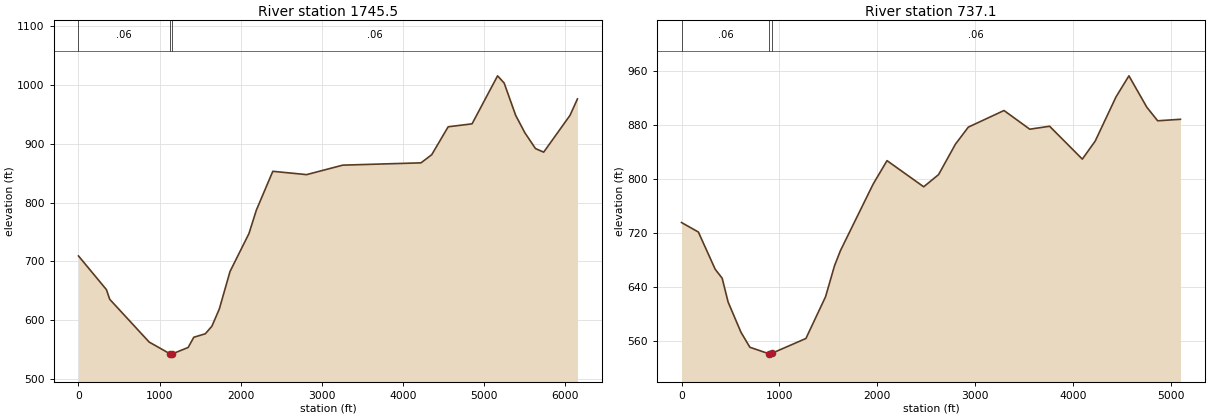
Type RM Length L Ch R = 1 ,1745.5  ,960.2,1008.5,1056.7
XS GIS Cut Line= 4
     1514610.623      437169.183     1514775.586      438117.719
     1515263.601       438158.96     1517405.924      442344.226
#Sta/Elev= 30
       0  709.25   344.6  651.93   385.1  635.51   871.6  562.73  1130.2  542.58
  1142.7  542.17  1155.2  542.46  1352.6  553.52  1422.5  570.91  1564.2  576.79
  1645.5  589.69  1736.9  618.94  1868.9  682.73  2102.4  747.28  2193.8  787.17
  2396.9  853.28  2813.3  847.63  3260.1  863.76  4224.8  867.67  4356.8  881.51
  4559.9  929.03  4854.4  934.06  5169.2 1015.75  5250.4 1003.46  5392.6  948.46
  5504.3  919.21  5636.3  892.02  5737.9  885.86  6062.8  948.52  6154.2  976.42
#Mann= 3 , 0 , 0
       0     .06       0  1130.2    .045       0  1155.2     .06       0
Bank Sta=1130.2,1155.2
XS Rating Curve= 0 ,0
Exp/Cntr=0.3,0.1

Type RM Length L Ch R = 1 ,737.1   ,714.5,737.1,759.7
XS GIS Cut Line= 4
      1514535.61      436988.898     1514473.133      437634.601
     1514252.475      438439.084     1512133.815      441372.504
#Sta/Elev= 30
       0  735.83   172.3   721.8   344.6  666.59   415.6  653.39   476.4   618.1
   608.2  573.29     699  551.15   897.5   541.3     910  540.97   922.5  542.11
  1271.9  564.14  1472.9  626.04    1564  671.74  1624.8  694.22  1959.3  792.79
  2101.2  827.48  2476.2  788.78  2628.3  806.83  2800.6  851.87  2932.3  877.12
  3297.2  901.73  3560.8  874.05  3763.5  878.42    4098  829.76  4229.7  856.49
  4442.6  921.91  4574.4  953.09  4756.8  906.73  4868.3  886.51  5101.4  888.73
#Mann= 3 , 0 , 0
       0     .06       0   897.5    .045       0   922.5     .06       0
Bank Sta=897.5,922.5
XS Rating Curve= 0 ,0
Exp/Cntr=0.3,0.1

Chan Stop Cuts=-1
Use User Specified Reach Order=0